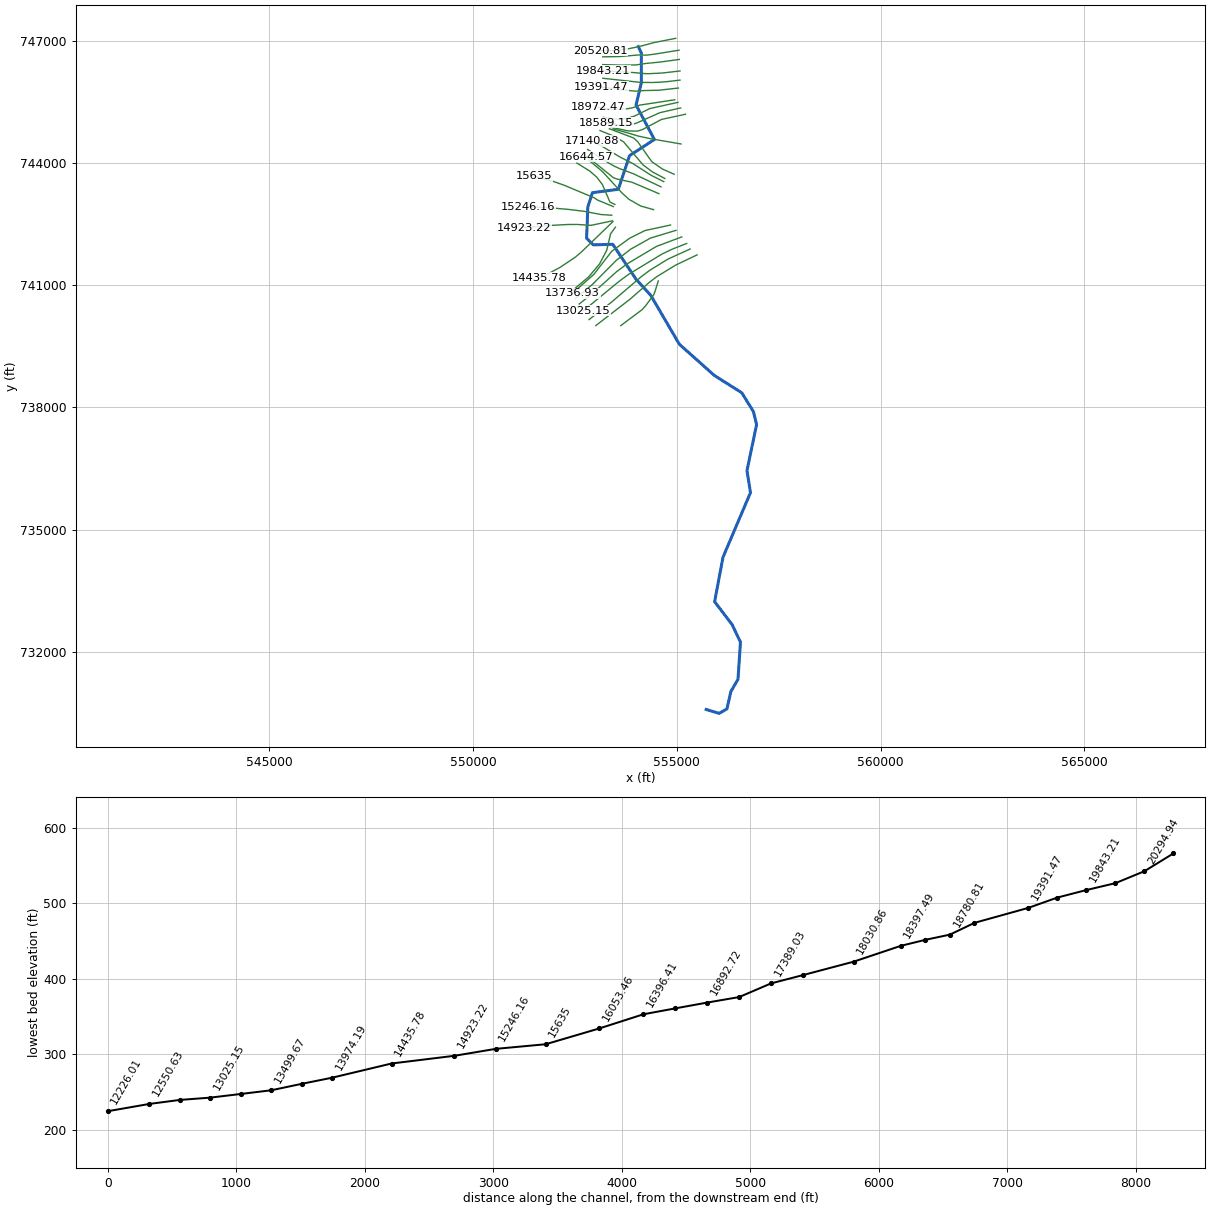
--- 1761_ras.prj (project) ---

Proj Title=1761
Current Plan=p01
Default Exp/Contr=0.3,0.1
English Units
Geom File=g01
Flow File=f01
Plan File=p01
Y Axis Title=Elevation
X Axis Title(PF)=Main Channel Distance
X Axis Title(XS)=Station
BEGIN DESCRIPTION:
RFD model 1761 exported to HEC-RAS
END DESCRIPTION:

--- 1761_ras.p01 (plan) ---

Plan Title=Plan 01
Program Version=4.10
Short Identifier=Plan 01
Geom File=g01
Flow File=f01
Subcritical Flow
Calc Critical at every XS
Secant Critical Depth

--- 1761_ras.f01 (steady flow) ---

Flow Title=Flow 01
Program Version=5.01
Number of Profiles= 6
Profile Names=10yr,25yr,50yr,100yr,100plus,500yr
River Rch & RM=1761,68,20520.81
 2976.95  4750.9 6418.88 7909.1511547.3613239.82
River Rch & RM=1761,68,20294.94
 2978.63 4753.68 6422.73 7913.9911554.4313247.15
River Rch & RM=1761,68,20069.08
 2988.35 4769.86 6445.18  7942.311595.7613290.17
River Rch & RM=1761,68,19843.21
 3007.59 4802.06 6490.05 7999.0311678.5913376.96
River Rch & RM=1761,68,19617.33
 3010.67 4807.19 6497.17 8008.0311691.7213390.65
River Rch & RM=1761,68,19391.47
 3014.07    4813 6505.37  8018.511707.0113407.06
River Rch & RM=1761,68,18972.47
 3022.55  4827.5 6525.83 8044.66 11745.213448.06
River Rch & RM=1761,68,18780.81
 3023.88 4829.77 6529.02 8048.7311751.1513454.44
River Rch & RM=1761,68,18589.15
 3025.39 4832.35 6532.66 8053.3811757.9413461.72
River Rch & RM=1761,68,18397.49
 3053.23 4878.74 6597.14 8134.7411876.7313585.29
River Rch & RM=1761,68,18030.86
 3177.68  5086.3 6885.73 8499.04 12408.614136.88
River Rch & RM=1761,68,17637.18
 3192.85 5112.95 6923.95 8548.56 12480.914216.26
River Rch & RM=1761,68,17389.03
 3208.84 5140.36 6962.71  8598.212553.3814293.69
River Rch & RM=1761,68,17140.88
 3216.85 5154.43 6982.86 8624.31 12591.514335.45
River Rch & RM=1761,68,16892.72
 3219.16 5158.54 6988.78 8632.0112602.7414347.88
River Rch & RM=1761,68,16644.57
 3236.64 5189.45 7033.26 8689.8312687.1514440.97
River Rch & RM=1761,68,16396.41
 3241.28 5197.66 7045.08  8705.2 12709.614465.75
River Rch & RM=1761,68,16053.46
 3243.59 5201.75 7050.98 8712.8812720.8114478.14
River Rch & RM=1761,68,   15635
 5069.86 8176.0611127.5413791.5820135.71 21611.4
River Rch & RM=1761,68,15246.16
 5074.89  8185.211140.8913809.1520161.36 21638.6
River Rch & RM=1761,68,14923.22
 5080.86 8196.1511156.9813830.4220192.4121671.83
River Rch & RM=1761,68,14435.78
 5083.88 8201.6611165.0613841.0820207.9821688.44
River Rch & RM=1761,68,13974.19
 5102.61 8236.08 11215.713908.0820305.7921793.25
River Rch & RM=1761,68,13736.93
 5103.28 8237.3111217.5213910.48 20309.321797.01
River Rch & RM=1761,68,13499.67
 5106.87 8243.9411227.2913923.4320328.2121817.35
River Rch & RM=1761,68,13262.41
 5121.54  8271.5 11268.313978.1920408.1621904.62
River Rch & RM=1761,68,13025.15
 5128.97 8285.4811289.12   1400620448.7621948.96
River Rch & RM=1761,68,12787.89
 5130.73 8288.9711294.4414013.2520459.3521960.98
River Rch & RM=1761,68,12550.63
 5133.16 8293.7611301.7714023.2220473.91 21977.5
River Rch & RM=1761,68,12226.01
 5136.03 8299.4511310.4414035.0220491.1321997.02
River Rch & RM=1761,68,12115.18
 5159.39 8343.3811375.8814122.4720618.8122136.45
River Rch & RM=1761,68,11790.87
 5202.08 8425.0711498.61 14287.620859.89 22403.1
River Rch & RM=1761,68,11544.37
 5204.96  8430.911507.6314299.9920877.9922423.96
River Rch & RM=1761,68,11297.87
 5228.28 8476.9111577.8114395.5421017.4822581.66
River Rch & RM=1761,68,11051.38
 5229.24 8478.9111580.9414399.8821023.8222589.09
River Rch & RM=1761,68,10804.88
 5230.58  8481.711585.3214405.9521032.6922599.49
River Rch & RM=1761,68,10558.38
 5231.91 8484.4911589.6914412.0221041.5422609.88
River Rch & RM=1761,68,10311.88
  5237.1 8495.2911606.5814435.4621075.7722649.96
River Rch & RM=1761,68,10065.38
 5273.33 8570.3111723.6714597.5921312.4822926.06
River Rch & RM=1761,68,9891.508
 5274.16 8572.0611726.4314601.44 21318.122932.71
River Rch & RM=1761,68,9801.378
 5274.53 8572.8411727.6614603.15 21320.622935.66
River Rch & RM=1761,68,9562.405
 5276.64 8577.3111734.7114612.9921334.9622952.64
River Rch & RM=1761,68,9323.433
 5277.43 8579.0111737.4214616.7921340.5222959.28
River Rch & RM=1761,68, 9084.46
 5284.16 8593.4111760.2114648.6921387.0923014.61
River Rch & RM=1761,68,8845.487
 5285.18 8595.6411763.7814653.7221394.4323023.46
River Rch & RM=1761,68,8606.514
 5287.29 8600.3611771.3914664.5221410.1923042.62
River Rch & RM=1761,68,8367.541
 5287.77 8601.4511773.15   1466721413.8323047.04
River Rch & RM=1761,68,8128.568
 5290.64 8607.9111783.6114681.8821435.5423073.57
River Rch & RM=1761,68,7889.595
 5293.42 8614.1911793.7814696.3421456.6523099.34
River Rch & RM=1761,68,7786.636
 5293.67 8614.7411794.6614697.5821458.4723101.55
River Rch & RM=1761,68,7720.608
 5293.91 8615.2811795.5414698.8321460.2923103.76
River Rch & RM=1761,68,7625.595
  5295.9 8619.76 11802.814709.1521475.3523122.16
River Rch & RM=1761,68,7399.003
 5327.59 8688.6811912.76 14863.9 21701.323393.12
River Rch & RM=1761,68, 7172.41
 5330.09 8694.2711921.7814876.6921719.9723415.83
River Rch & RM=1761,68,6945.817
  5331.8 8698.0711927.9114885.3721732.6523431.21
River Rch & RM=1761,68,6719.224
 5337.65 8711.2611949.2714915.75   2177723485.36
River Rch & RM=1761,68,6388.935
 5340.48 8717.5711959.4414930.1821798.0723510.96
River Rch & RM=1761,68,6071.463
 5343.86 8725.1211971.6214947.4721823.3123541.66
River Rch & RM=1761,68,5789.315
  5345.8 8729.3611978.4114957.0421837.2923558.46
River Rch & RM=1761,68, 5564.86
 5346.59 8731.06 11981.114960.8321842.8123565.04
River Rch & RM=1761,68,5340.406
 5346.77 8731.4411981.7114961.6721844.04 23566.5
Boundary for River Rch & Prof#=1761,68,1
Up Type= 0
Dn Type= 2
Boundary for River Rch & Prof#=1761,68,2
Up Type= 0
Dn Type= 2
Boundary for River Rch & Prof#=1761,68,2
Up Type= 0
Dn Type= 2
Boundary for River Rch & Prof#=1761,68,2
Up Type= 0
Dn Type= 2
Boundary for River Rch & Prof#=1761,68,2
Up Type= 0
Dn Type= 2
Boundary for River Rch & Prof#=1761,68,2
Up Type= 0
Dn Type= 2

--- 1761_ras.g01 (geometry) ---

Geom Title=1761
Program Version=4.10

River Reach=1761,68
Reach XY= 30
554053.198099702746850.864947285 554128.26274058746693.704503542
554128.495343892 745966.05968751553998.587602914745419.416536506
554448.160310207744572.274520177553838.791074902744176.781555896
553563.985922812743351.462600362552929.022983431743268.034528163
552815.552120118742918.882586646552784.446657659742150.361407435
552948.944632591741988.012397102553426.838493048742001.283079283
553997.708227428741144.885382142 554359.46001455740749.089070161
555059.475515125 739551.10345424555917.550703884738785.034232156
556591.474328963738359.267788154556877.678849667737898.316147236
556955.589167239737576.112835905556719.441425352736448.794896874
556805.728504925735909.506068534556131.603965698734324.407190707
555925.807851554733233.620740939556356.105558427732669.376847706
556560.258008183732240.638992769556499.070988359731325.513005805
556325.210155069731032.063693565556228.071090607 730602.72544576
556036.414280025730492.855669047 555719.32415059 730588.59229552

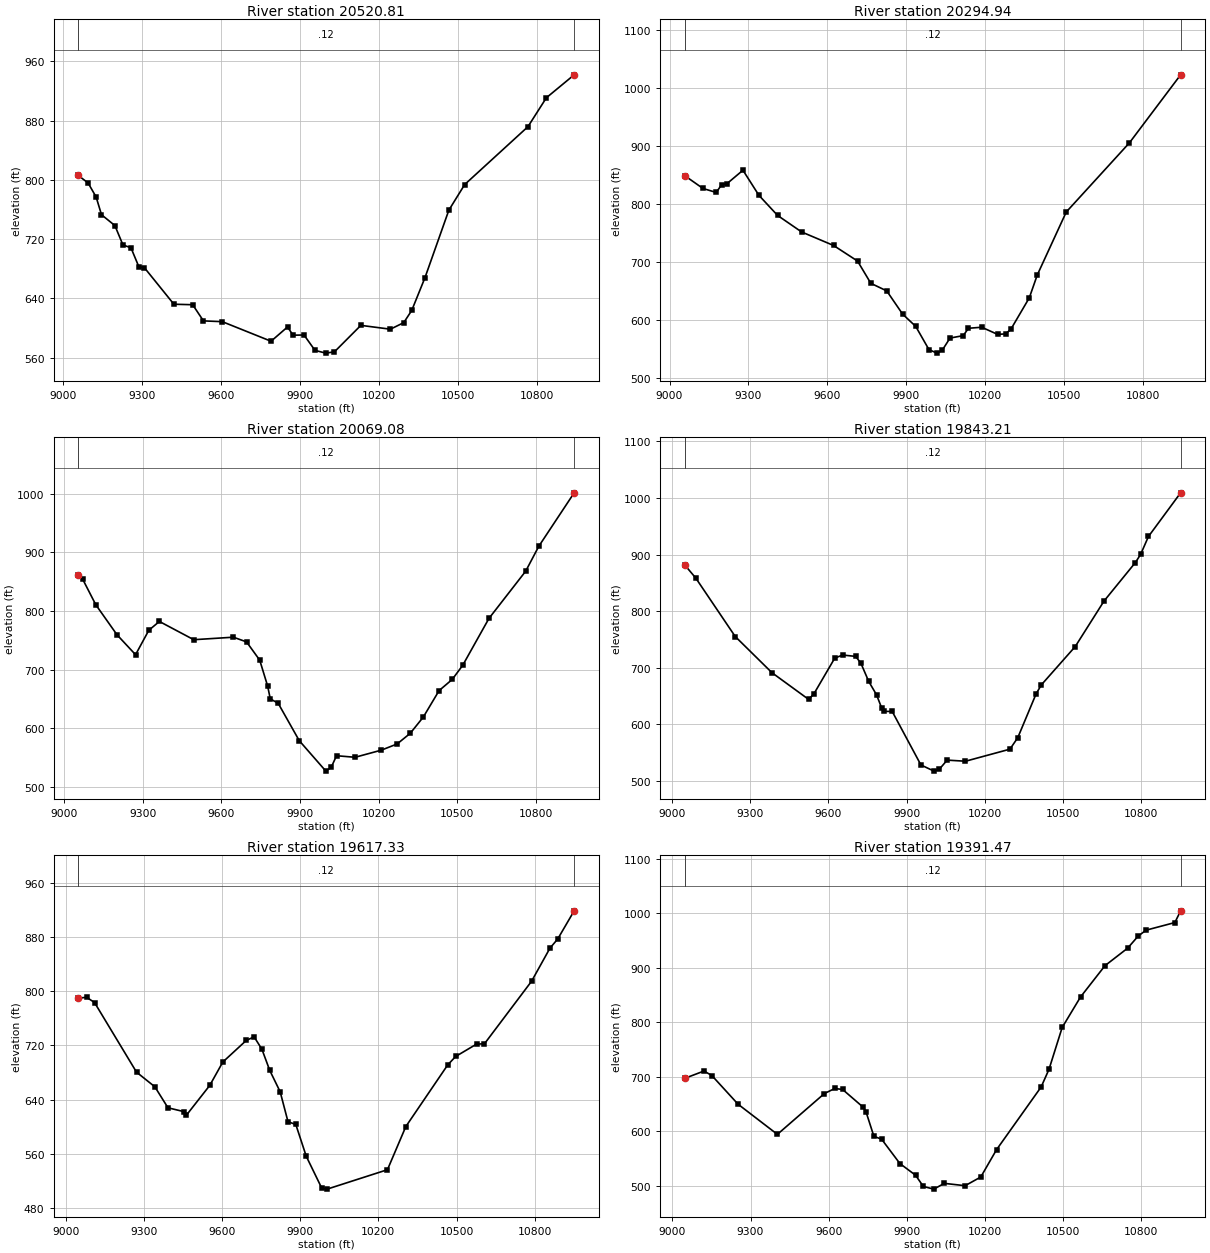
Type RM Length L Ch R = 1 ,20520.81,225.870000,225.870000,225.870000
XS GIS Cut Line= 6
554971.467151882747054.826535842554447.523832736 746952.67383458
 554081.52688499746854.616656451553809.960003049746798.363118401
553475.480868482746762.220352409553119.530275974746751.746723124
#Sta/Elev= 30
9058.477805.9575 9095.58795.83249126.102776.88229146.451 753.0089197.322738.3417
9227.845712.23839258.368708.3518 9288.89682.24979309.239681.53469421.355632.1692
9492.807631.48859533.636609.68299605.149608.63369790.426582.20899853.004 601.504
9873.863590.37499915.581 590.626  9957.3569.87149998.265566.156710031.22567.9321
10131.43603.641310243.69598.467710294.29607.307910324.63623.731410375.02668.0857
10465.51759.043910525.71793.711110766.04871.852610836.05910.898310941.53941.8474
#Mann= 3 , 0 , 0
9058.477    0.12       09058.477    0.12       010941.53    0.12       0
#XS Ineff= 2 , 0
       0                               0
Bank Sta=9058.477,10941.53
Exp/Cntr=0.3,0.1

Type RM Length L Ch R = 1 ,20294.94,225.870000,225.870000,225.870000
XS GIS Cut Line= 6
555053.100451802746764.196026995554489.469213527746672.577737262
554266.512660619746643.168212635554047.972519617746646.018986711
553605.116334672746608.201409066553180.515805549 746601.16859802
#Sta/Elev= 30
9057.995848.37089126.989826.39969177.645819.47789197.908833.0638 9218.17834.6294
9278.958857.82049339.745 814.5069410.664779.88469501.845751.4399 9623.42728.1025
9714.363701.29259764.879662.9184 9825.27649.86369885.483609.93329935.537588.5988
9985.636548.749910015.71542.598110035.75 547.24410065.75568.571310115.86572.7294
10135.93585.448510186.18587.213110246.49574.921910276.64575.739710296.74583.5284
10367.07637.970110397.14677.0703 10507.4785.775610747.55905.071810942.031022.236
#Mann= 3 , 0 , 0
9057.995    0.12       09057.995    0.12       010942.03    0.12       0
#XS Ineff= 2 , 0
       0                               0
Bank Sta=9057.995,10942.03
Exp/Cntr=0.3,0.1

Type RM Length L Ch R = 1 ,20069.08,225.870000,225.870000,225.870000
XS GIS Cut Line= 6
555060.819325601746537.539646104554619.241529636746476.520814138
554210.055970446746435.215191255553996.792320802746402.085781246
553641.081146305746397.541259452553180.396589817746410.702740655
#Sta/Elev= 30
9055.127860.62889071.115 854.7379121.646810.65159202.495759.39399273.238725.3915
9323.678767.03029364.015782.12739495.108750.99179646.021755.26789696.259747.2627
9746.489716.07939776.626671.89169786.672 650.115 9816.81642.50499897.177578.6888
9998.566526.767410018.92533.319510039.27 553.04610109.85550.392510210.03562.5811
10270.05 573.09910320.05591.232210370.05619.087610430.05664.155810480.05683.1648
10520.05707.254710620.07787.277710760.13867.913410810.16910.424510944.861001.579
#Mann= 3 , 0 , 0
9055.127    0.12       09055.127    0.12       010944.86    0.12       0
#XS Ineff= 2 , 0
       0                               0
Bank Sta=9055.127,10944.86
Exp/Cntr=0.3,0.1

Type RM Length L Ch R = 1 ,19843.21,225.870000,225.870000,225.870000
XS GIS Cut Line= 6
555076.785535425 746253.87762605554633.576796234746203.165742522
554296.238613577746187.170270485554188.807437477746190.988971662
553948.280320388746214.476089474553181.895679664746262.912939045
#Sta/Elev= 30
9049.511881.41679091.633 858.3949242.842755.26679383.654691.40169524.287644.2628
9544.331653.92659624.507717.14729654.572 722.5759704.637720.16519724.643708.1315
9754.652675.99419784.661652.34789804.667628.7029 9814.67623.13029844.683623.0145
9954.818528.566110005.08517.662210025.21520.9164 10055.4537.085810125.72535.1396
10296.14556.4209 10326.2576.696310396.34653.943310416.38 669.83510546.64737.6253
10656.86817.8637 10777.1885.829310797.14 900.192 10827.2931.796610950.551008.873
#Mann= 3 , 0 , 0
9049.511    0.12       09049.511    0.12       010950.55    0.12       0
#XS Ineff= 2 , 0
       0                               0
Bank Sta=9049.511,10950.55
Exp/Cntr=0.3,0.1

Type RM Length L Ch R = 1 ,19617.33,225.870000,225.870000,225.870000
XS GIS Cut Line= 6
555076.681502263 746030.25853615554812.160232985745998.286722922
554561.914471199745977.304310191554375.094682704745971.148845743
554108.320512595745973.845893326553182.428724181746075.158533594
#Sta/Elev= 30
9048.577789.67749080.489790.85769110.707783.15289271.871680.40169342.311658.7511
9392.545627.79019452.777622.20649462.804616.59959553.044660.86439603.115695.3518
9693.185727.2413 9723.19 732.4839753.195714.12149783.199682.93849823.204651.3502
9853.208607.24749883.211 603.1339923.216556.24919983.222508.801410003.22507.7214
10234.89 536.38110305.37600.042510466.43691.191410496.58703.501310576.98721.8137
10607.13722.226610788.04 814.59210858.39863.312210888.54877.052410951.42918.4959
#Mann= 3 , 0 , 0
9048.577    0.12       09048.577    0.12       010951.42    0.12       0
#XS Ineff= 2 , 0
       0                               0
Bank Sta=9048.577,10951.42
Exp/Cntr=0.3,0.1

Type RM Length L Ch R = 1 ,19391.47,419.000000,419.000000,419.000000
XS GIS Cut Line= 6
555038.110783734745835.507586941554563.248734666745781.901442479
554193.073656172745773.480730975553987.269502247745759.341177999
553894.284519082745766.260248066553143.059149687745859.234567853
#Sta/Elev= 30
9047.556697.24189121.249710.61099151.488702.37019252.285649.72859403.216594.4707
9583.816669.31149623.865678.59889653.901676.78179733.917643.81699743.918635.5868
9773.918591.03349803.919585.4574 9873.92540.96159933.993519.57219964.143498.9273
10004.36494.051810044.45504.628910124.52500.322510184.73516.304510245.21 566.374
10416.69681.464310446.95713.990510497.36790.436710567.85846.360510661.86903.7928
10749.11936.010310789.39958.082510819.61968.885110930.38982.879310952.471004.379
#Mann= 3 , 0 , 0
9047.556    0.12       09047.556    0.12       010952.47    0.12       0
#XS Ineff= 2 , 0
       0                               0
Bank Sta=9047.556,10952.47
Exp/Cntr=0.3,0.1

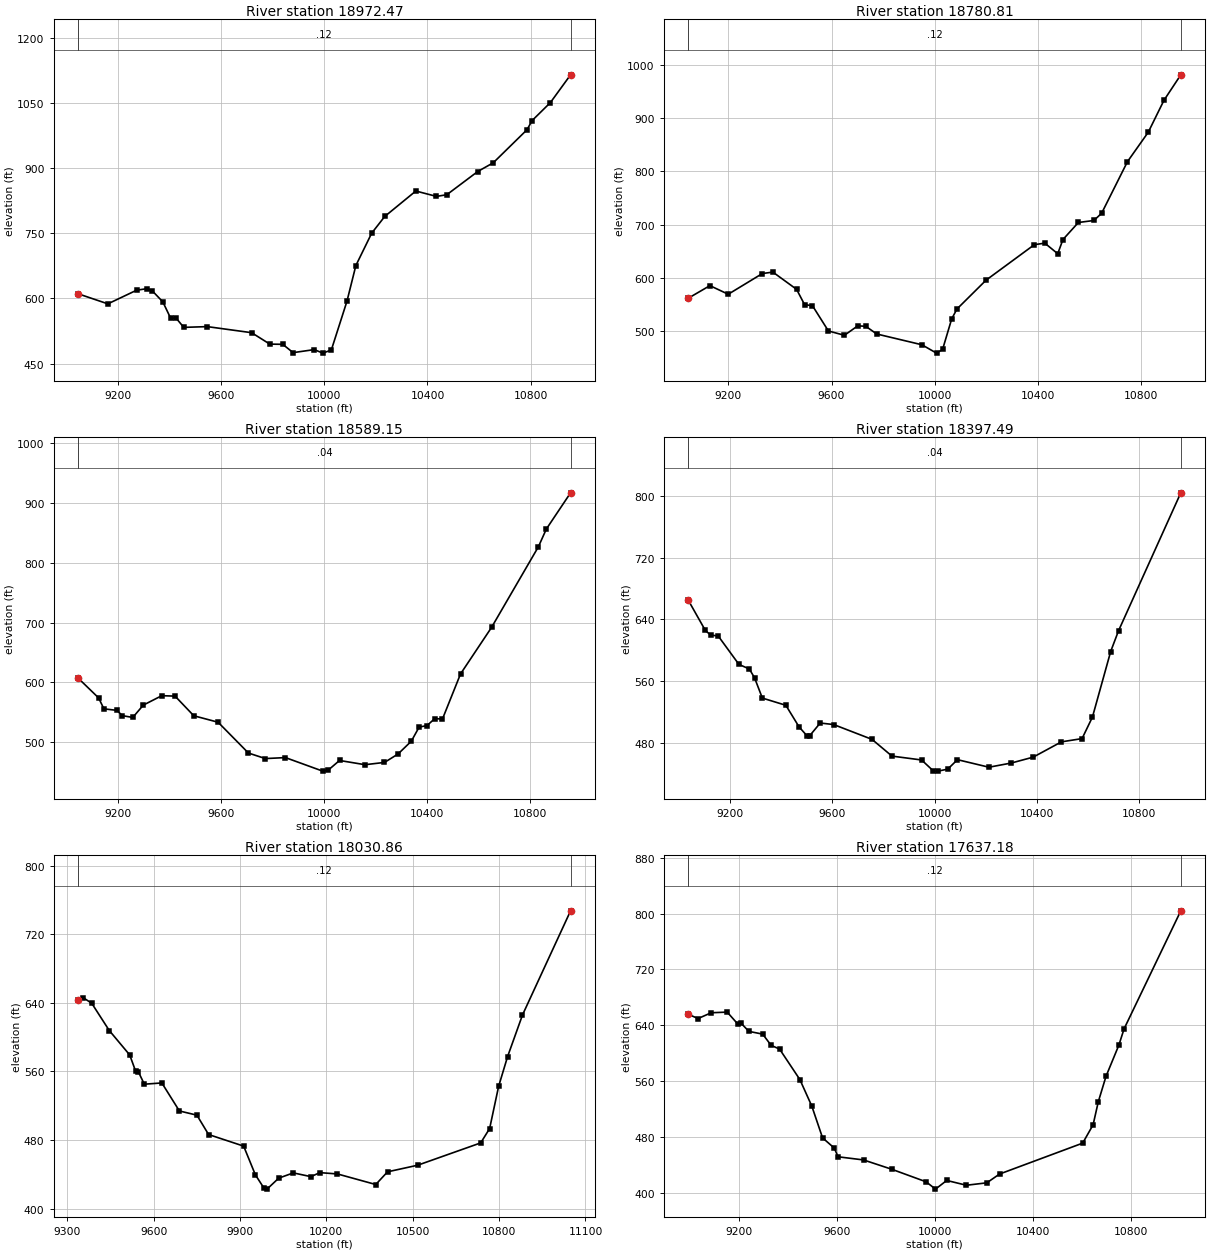
Type RM Length L Ch R = 1 ,18972.47,191.657400,191.657400,191.657400
XS GIS Cut Line= 6
554948.510772598 745548.05567504554083.884678693 745415.64403492
553915.862373604745350.777426396553734.697146149745318.649089008
553410.372570635745315.659945048553067.751470645745358.523773987
#Sta/Elev= 30
9045.043610.79459160.241587.66499271.877619.10889312.471 622.6439332.768617.4476
9373.363592.31169403.809554.58339424.106555.41859454.552533.5359 9545.89535.2655
  9717.9521.27869788.366495.00629838.611494.53089878.806475.37469960.817482.3598
9994.179474.253310027.08481.523710087.52593.462310122.19675.869510183.58750.3589
10234.13 788.76210354.76847.369810434.83834.995810474.84838.811410594.93892.2856
10655.15912.401510785.88988.354710806.04 1009.6610876.841051.019   109551114.809
#Mann= 3 , 0 , 0
9045.043    0.12       09045.043    0.12       0   10955    0.12       0
#XS Ineff= 2 , 0
       0                               0
Bank Sta=9045.043,10955
Exp/Cntr=0.3,0.1

Type RM Length L Ch R = 1 ,18780.81,191.657500,191.657500,191.657500
XS GIS Cut Line= 6
555027.273893468745484.272190045554336.965429616745331.754893295
553959.644106348745147.478029935553776.879585453745090.218246346
553497.779301225745073.598842042553190.571405761745114.614088359
#Sta/Elev= 30
9044.571561.87149128.124585.36919199.213569.19639331.683608.09959372.531610.7699
9464.507578.40219495.365549.76939526.222547.59649587.936500.25279650.078492.1529
9702.067509.9296 9733.26508.95699775.292494.58459950.831 474.33610007.43458.6368
10031.02 465.49410066.41522.984110086.88 541.51110199.62  595.5910387.11662.2556
10427.61665.172810477.93 645.29710497.98671.850110558.03 703.95910618.05 707.684
10648.07721.139410748.49818.2132 10829.2873.489110890.01933.283910955.43981.2141
#Mann= 3 , 0 , 0
9044.571    0.12       09044.571    0.12       010955.43    0.12       0
#XS Ineff= 2 , 0
       0                               0
Bank Sta=9044.571,10955.43
Exp/Cntr=0.3,0.1

Type RM Length L Ch R = 1 ,18589.15,191.657400,191.657400,191.657400
XS GIS Cut Line= 6
555093.394521634745347.578541967554582.889155634745230.693994978
554018.261189419744978.560551235553881.565183136744934.958740204
553628.262920012744920.838000681553262.903250058744980.515731191
#Sta/Elev= 30
  9044.1607.1259 9123.67574.0086 9143.97555.81979194.848553.25389215.282 544.431
9256.149541.43289297.016562.04269368.702577.78039420.273  577.079493.028544.2415
 9587.35533.44279705.151481.95489770.872472.70389848.834474.35779993.549451.7351
 10015.2453.473310058.78469.545610157.79462.473610233.44466.270810285.99480.3562
10337.51501.714710367.93525.326110398.34527.792110428.48539.424410458.55 538.847
10528.57614.091410648.93691.772410831.13826.765910861.74856.1946 10955.9916.7391
#Mann= 3 , 0 , 0
  9044.1    0.04       0  9044.1    0.04       0 10955.9    0.04       0
#XS Ineff= 2 , 0
       0                10072.99       0
Bank Sta=9044.1,10955.9
Exp/Cntr=0.3,0.1

Type RM Length L Ch R = 1 ,18397.49,366.630600,366.630600,366.630600
XS GIS Cut Line= 6
555210.724722626745192.204792786554621.588203799745064.653516772
554154.423124318744815.773896003554030.038281364744777.393911133
553799.579324904744783.919608037553377.797591293744875.438087072
#Sta/Elev= 30
9036.031664.66529102.493625.77829122.717619.93399153.053  618.529233.986581.8416
9274.622575.9389 9294.97564.62599325.598538.28189417.686528.94689469.302501.0268
9500.272 489.5079510.595489.39859552.204505.99889604.758504.02259755.092484.8285
9833.119463.18639949.222458.16289995.725443.800210013.54443.744910051.56446.3514
10089.55458.566410212.75448.805410300.83454.275510386.13461.853210496.53481.6303
10577.34485.822710618.05513.728310689.37598.479210720.08625.336810963.94803.8651
#Mann= 3 , 0 , 0
9036.031    0.04       09036.031    0.04       010963.94    0.04       0
#XS Ineff= 2 , 0
       0                10093.85       0
Bank Sta=9036.031,10963.94
Exp/Cntr=0.3,0.1

Type RM Length L Ch R = 1 ,18030.86,393.677600,393.677600,393.677600
XS GIS Cut Line= 6
555101.458214611744463.304197863554346.249881297744593.512531221
554037.370806724744660.498354629553933.932765424744693.709657654
553746.489913374744748.037257373553433.854055017744833.652515352
#Sta/Elev= 30
9337.833643.20779354.534646.17619384.977639.48489445.862607.72249516.895579.2359
 9537.19560.51379547.338559.31799567.633 545.1369628.518546.60069689.403513.9379
9750.289509.02699790.879486.45259912.649 472.9459953.239439.55339983.682423.6864
 9993.83422.798510034.42435.585310085.16441.731510146.39437.338710177.09442.0379
10238.49440.483910371.51428.182210412.44442.965510517.26 450.69510735.95476.6933
10767.06493.433610798.16542.516210829.27577.185110881.11625.808611048.19747.2673
#Mann= 3 , 0 , 0
9337.833    0.12       09337.833    0.12       011048.19    0.12       0
#XS Ineff= 2 , 0
       0                10089.92       0
Bank Sta=9337.833,11048.19
Exp/Cntr=0.3,0.1

Type RM Length L Ch R = 1 ,17637.18,248.154100,248.154100,248.154100
XS GIS Cut Line= 6
554931.896465548743719.893333638554650.381370366743845.495962486
554384.113425831744028.632141457554040.585450352744515.515900803
553940.654352506744609.362313048553343.473371343744836.273220611
#Sta/Elev= 30
8995.014655.67239034.567649.62269088.166657.92999153.525658.86169197.595641.4106
9208.676643.47579241.969631.23329298.342 627.2869332.701611.22079367.298605.8556
9450.122562.14899498.882524.06259542.719478.56519590.459463.96139606.079451.4138
9709.869446.92289825.951433.46029965.482415.5414 10003.7405.061210049.61417.5081
10129.91410.618110213.27414.100910265.11426.679910604.56471.020110647.06497.3213
10668.14530.176910699.77566.823210752.46611.763810773.37634.7676   11005804.0613
#Mann= 3 , 0 , 0
8995.014    0.12       08995.014    0.12       0   11005    0.12       0
#XS Ineff= 2 , 0
       0                10062.18       0
Bank Sta=8995.014,11005
Exp/Cntr=0.3,0.1

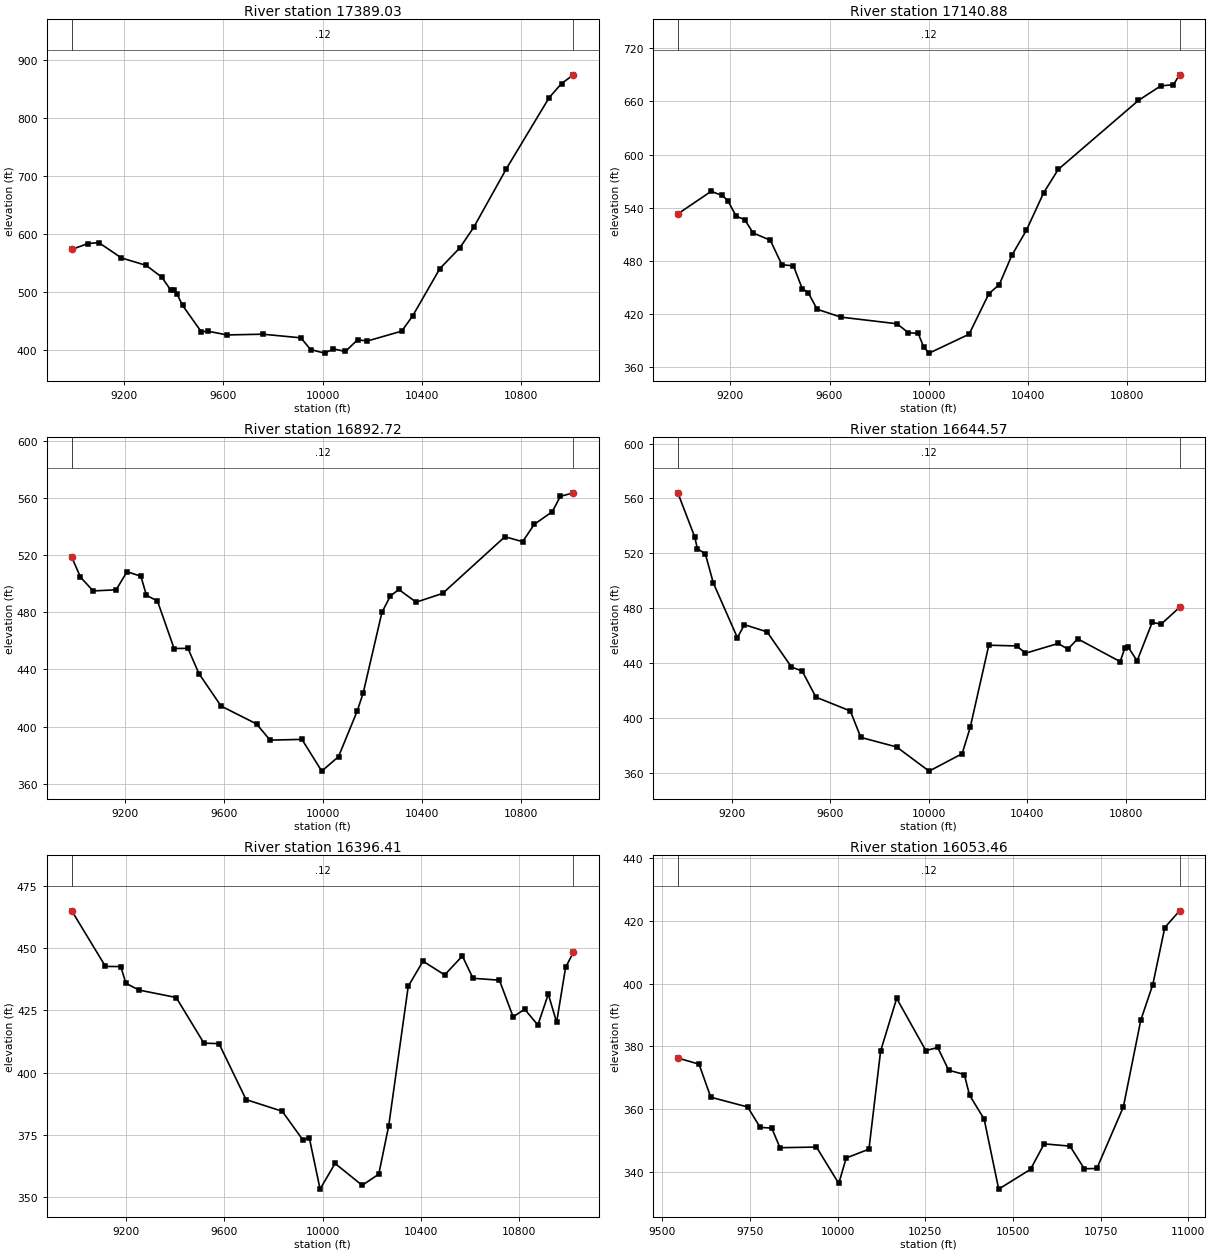
Type RM Length L Ch R = 1 ,17389.03,248.154100,248.154100,248.154100
XS GIS Cut Line= 6
554704.182008654743616.787350078554398.631845772 743779.08030531
554169.137028763743949.960312872553692.615318964744515.258836618
553449.817032981744656.843551143553113.846912726744792.213347365
#Sta/Elev= 30
8990.111573.20129055.318583.41919099.563584.93959189.837558.55049289.564545.7504
9352.681525.27719388.537502.9625 9401.38503.18839412.989497.07489436.142476.6532
 9511.94430.77179537.221432.10899615.125425.51389758.911426.79569912.572420.5211
9951.633400.241110007.86394.101510043.85401.374210091.84396.9492 10141.3417.3681
10178.95414.878310318.54432.124910362.91458.641810472.01540.114610552.14 575.776
10608.53611.544110740.02712.798310912.17 835.49410961.99859.832611009.86874.8466
#Mann= 3 , 0 , 0
8990.111    0.12       08990.111    0.12       011009.86    0.12       0
#XS Ineff= 2 , 0
       0                 10129.8       0
Bank Sta=8990.111,11009.86
Exp/Cntr=0.3,0.1

Type RM Length L Ch R = 1 ,17140.88,248.154100,248.154100,248.154100
XS GIS Cut Line= 6
554677.371446823743539.185274029554369.860992099743693.270567506
553926.405987314743978.621162629553618.141636228744134.754484332
553180.580766657744395.801594314552917.549581955744536.195978129
#Sta/Elev= 30
8987.524532.99319121.916558.43359167.004553.7911 9189.15548.08879223.031530.4101
9257.291526.64159291.551511.51289360.771503.35469407.577475.71679454.383474.4018
9489.707448.78819513.753444.28279549.823425.4701 9646.01416.6069 9872.15409.1257
9917.771399.07499957.984398.16839980.173382.6789 10002.1376.007710163.18397.3372
10243.06443.016810285.13 453.30210335.72486.285910394.25514.435810464.48 556.978
10523.01583.180510846.49660.932710936.61677.366910988.06678.7717 11012.5689.8611
#Mann= 3 , 0 , 0
8987.524    0.12       08987.524    0.12       0 11012.5    0.12       0
#XS Ineff= 2 , 0
       0                 10510.2       0
Bank Sta=8987.524,11012.5
Exp/Cntr=0.3,0.1

Type RM Length L Ch R = 1 ,16892.72,248.154100,248.154100,248.154100
XS GIS Cut Line= 6
 554609.31013381743411.665308717553940.592623513743729.255652949
553602.790089209743854.945738569553477.182981648743911.740469039
 553329.44259838743995.926127121552809.353330006 744328.41633688
#Sta/Elev= 30
8986.748 518.7639021.667504.80049073.005495.05099166.098495.8334 9210.06508.5452
9265.966505.32489288.329492.04529333.054487.93229400.142454.68219456.048454.7979
9500.773437.02459589.957414.34529733.321401.80529787.607390.47559916.446 390.997
9996.541368.742310064.21378.888510139.75410.809410164.01 423.55110239.59479.9926
10273.64491.4988 10307.9496.058610377.73 487.15410484.94493.313710736.28533.0354
10807.92529.572810854.93541.746310927.56550.549210960.42561.338911013.24 563.811
#Mann= 3 , 0 , 0
8986.748    0.12       08986.748    0.12       011013.24    0.12       0
#XS Ineff= 2 , 0
       0                 10295.1       0
Bank Sta=8986.748,11013.24
Exp/Cntr=0.3,0.1

Type RM Length L Ch R = 1 ,16644.57,248.154100,248.154100,248.154100
XS GIS Cut Line= 6
554559.622878449743243.702853291553893.061259888743526.231651463
553534.693165664743601.603299252553443.567483667743635.539160102
553000.410346133743992.238791544552772.815829272744153.390587984
#Sta/Elev= 30
8981.108564.09349049.991531.81179060.651523.33769092.946519.54139125.262498.3915
9223.154 458.3779251.502467.90499343.547462.67059442.478437.05359486.448434.0241
9541.939415.04299681.825404.94319724.321385.67859869.946378.684910001.72361.0585
10135.87373.758210168.63392.888810244.21452.921910357.49452.397610393.25447.0646
10525.82 454.18210565.59  450.0310604.95457.606410777.79440.947510796.61450.7206
10809.11451.857610846.61 441.51910907.99469.576810944.25468.270411018.81480.4985
#Mann= 3 , 0 , 0
8981.108    0.12       08981.108    0.12       011018.81    0.12       0
#XS Ineff= 2 , 0
       0                10289.71       0
Bank Sta=8981.108,11018.81
Exp/Cntr=0.3,0.1

Type RM Length L Ch R = 1 ,16396.41,342.951800,342.951800,342.951800
XS GIS Cut Line= 6
554428.742888661742852.118473748 554111.84695022742941.136143546
  553821.2710293743107.296113187553651.904959588743262.481266798
553175.112160974743784.633434268552839.250203635744065.532943724
#Sta/Elev= 30
8979.573464.98329116.708442.66999178.951442.60019199.918435.89539252.542 433.187
9404.396430.18359517.236411.84769578.498411.6778 9688.83389.18139835.789 384.512
 9919.07373.08169946.189373.73039989.714353.249910050.67 363.56110160.93354.7848
10228.46359.264310268.91378.672510348.46434.711710408.46444.766410496.47439.2538
10568.59446.8365 10611.8437.9003 10719.3437.132210775.15422.400510821.83425.4893
10875.73419.129110918.14 431.55810951.95420.228810988.51442.278411020.45448.3895
#Mann= 3 , 0 , 0
8979.573    0.12       08979.573    0.12       011020.45    0.12       0
#XS Ineff= 2 , 0
       09872.885        10382.78       0
Bank Sta=8979.573,11020.45
Exp/Cntr=0.3,0.1

Type RM Length L Ch R = 1 ,16053.46,418.461500,418.461500,418.461500
XS GIS Cut Line= 6
553479.465843737742979.467147827553357.877426952743038.702530354
553173.164203882743466.724036351553034.914990515743648.796017364
552862.056367874743798.774836242552548.114036709743993.325671792
#Sta/Elev= 30
9544.473376.30739605.059374.34939638.429363.81449743.627360.7017 9779.37354.2023
9812.332353.97719835.852347.72719939.944347.928510003.48336.320410024.67344.4458
 10089.6347.263210122.84378.5192 10168.7395.311310251.89378.661910285.62379.6614
10316.99372.425610361.55371.0512 10376.4364.485110418.09356.8599 10459.6334.5263
10550.33340.827310589.25348.945610662.98348.2324 10703.8341.019210739.53341.1088
10815.19360.726510864.85388.374210899.12399.711410933.29417.863810975.29423.2094
#Mann= 3 , 0 , 0
9544.473    0.12       09544.473    0.12       010975.29    0.12       0
#XS Ineff= 2 , 0
       09822.295        10151.73       0
Bank Sta=9544.473,10975.29
Exp/Cntr=0.3,0.1

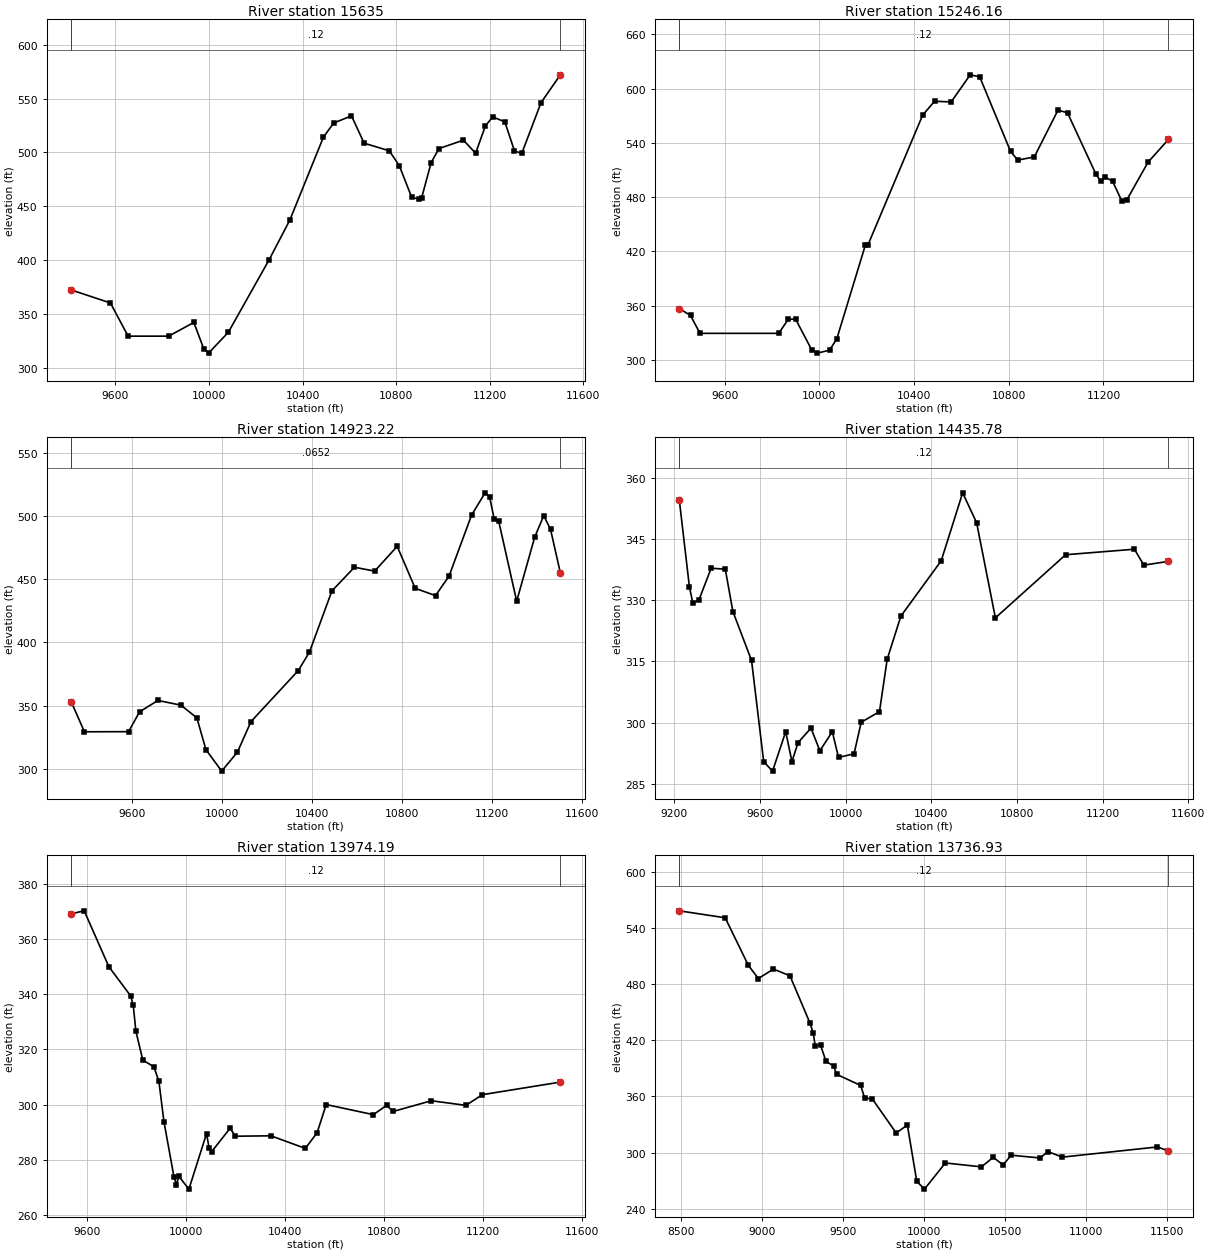
Type RM Length L Ch R = 1 ,   15635,388.840000,388.840000,388.840000
XS GIS Cut Line= 6
553440.067133814742926.935534552553051.630935967743087.567044944
552972.578654855 743141.38362357552234.162632763743450.826942444
551953.050677866743549.511952698551494.472346663743671.949059799
#Sta/Elev= 30
 9410.96372.29679578.763360.17869654.512  329.339827.653  329.339935.374342.0535
9978.065317.3345 9998.14313.563210082.87332.972310257.31 400.43610345.78437.3193
10489.06514.242810532.86527.329510608.94533.981110662.98508.5922 10770.5501.5184
10813.16487.719910866.47458.203610898.11 456.66610908.65457.777710949.43490.6353
10982.46503.585511087.22511.381411139.35499.270711181.05524.632611212.32532.9898
11264.11528.421811305.48501.413811336.49499.049511418.71546.174311501.47572.0929
#Mann= 3 , 0 , 0
 9410.96    0.12       0 9410.96    0.12       011501.47    0.12       0
#XS Ineff= 2 , 0
       09903.752        10256.84       0
Bank Sta=9410.96,11501.47
Exp/Cntr=0.3,0.1

Type RM Length L Ch R = 1 ,15246.16,322.937600,322.937600,322.937600
XS GIS Cut Line= 6
553402.493826581742714.442740018553139.276482539742732.041463449
552715.120854958742811.854301156552349.348272102742856.862729239
551843.727345857742900.261051207 551348.74882084742924.647969565
#Sta/Elev= 30
9407.626356.75069455.149 349.1019495.172  329.339827.702  329.339868.411344.7967
9898.944345.21719967.138311.15049991.562 307.45310042.72310.773110073.16323.0527
10194.38427.163910204.47426.711410436.13570.567710486.43585.901210556.76585.1984
10637.14615.139410677.32612.901210807.75530.410110837.84520.839810908.04524.3838
11008.29576.150411048.36573.123311168.54505.288211188.58497.391611208.61501.8551
11238.65497.5102 11278.7 475.15711298.72476.760911388.79518.579211475.11543.7251
#Mann= 3 , 0 , 0
9407.626    0.12       09407.626    0.12       011475.11    0.12       0
#XS Ineff= 2 , 0
       09887.509                       0
Bank Sta=9407.626,11475.11
Exp/Cntr=0.3,0.1

Type RM Length L Ch R = 1 ,14923.22,487.439500,487.439500,487.439500
XS GIS Cut Line= 6
 553422.71677801742578.430987343552893.986809633742466.434441691
552569.354630172742488.033257365552330.452685386 742487.69220525
551940.808304816742467.040495649551261.259736538742413.642217115
#Sta/Elev= 30
9328.429353.2227 9387.62  329.339583.891329.41929632.854345.09129714.598354.0958
9816.778350.39399887.944340.30989928.056315.26319998.252298.235810068.43313.2909
10128.54337.375310338.64377.645310388.65392.2696 10488.7440.666110588.79 459.385
10678.95456.345510779.14475.916110859.32442.751310949.57436.950811009.74452.3678
11110.02500.6135 11170.2518.208811190.27514.940111210.34497.7392 11230.4495.9882
11310.67432.571811390.94483.215911431.07500.159911461.17489.434111505.06454.9164
#Mann= 3 , 0 , 0
9328.429  0.0652       09328.429  0.0652       011505.06  0.0652       0
#XS Ineff= 2 , 0
       09869.107                       0
Bank Sta=9328.429,11505.06
Exp/Cntr=0.3,0.1

Type RM Length L Ch R = 1 ,14435.78,461.597300,461.597300,461.597300
XS GIS Cut Line= 6
553430.784704357742557.684890956552643.908136874741800.362992242
552507.948555171741685.760503501552143.361563802741441.610094607
551883.037180811741299.902262598551630.676132321741179.237528324
#Sta/Elev= 30
9222.476354.67419269.904333.27069285.661329.36539313.437329.94199371.479337.8482
9437.464337.60729473.054327.22569560.118 315.2239616.868290.38929658.269288.0771
9719.736297.75839748.757290.42199777.779295.09219837.673298.62719879.353293.0863
9937.396297.73649966.418291.439610038.97292.324810072.28300.054310157.71302.6654
10193.92315.553810257.79326.105710446.05339.660410546.31356.339210611.56349.0048
10699.24325.6673 11027.3341.154711348.66342.507111392.79338.604711507.86339.5238
#Mann= 3 , 0 , 0
9222.476    0.12       09222.476    0.12       011507.86    0.12       0
#XS Ineff= 2 , 0
       09546.136        10067.12       0
Bank Sta=9222.476,11507.86
Exp/Cntr=0.3,0.1

Type RM Length L Ch R = 1 ,13974.19,237.259200,237.259200,237.259200
XS GIS Cut Line= 6
553492.425717115742422.747133449553372.646595716742256.631210431
553279.267642528741856.341206282 553101.35130924741517.673209861
552834.312976062741200.891440645552407.682070136740840.697415173
#Sta/Elev= 30
9535.984369.15489588.819370.22989688.471349.95389776.161339.42139786.847335.9833
9797.533326.55129825.607316.08449870.088313.69369890.451308.42329910.814293.8228
 9951.17273.84869961.247 270.9819971.324273.933210011.71269.314410082.98289.4698
10093.28284.197510103.59 282.90610177.95291.376210199.58288.499710342.87288.6481
10482.11 284.08510529.58289.781110566.19299.980110756.88296.314310809.88299.6949
 10836.8 297.47810990.73301.361511130.55299.6922   11197303.564911512.04 308.128
#Mann= 3 , 0 , 0
9535.984    0.12       09535.984    0.12       011512.04    0.12       0
#XS Ineff= 2 , 0
       0                10184.02       0
Bank Sta=9535.984,11512.04
Exp/Cntr=0.3,0.1

Type RM Length L Ch R = 1 ,13736.93,237.259200,237.259200,237.259200
XS GIS Cut Line= 6
 554844.87746713742474.683614851554215.041902466742338.421492298
553839.729031129742149.285521441553401.428501138741831.069107825
552960.776416795741260.951236601552440.368643207740803.043789493
#Sta/Elev= 30
8487.633558.05878771.545550.6443 8914.71499.94028976.508485.85649069.996495.9301
9171.851488.78459294.448438.88699316.623427.36789327.711414.05579361.262414.6865
9395.278397.37719441.378392.63589461.203383.56399609.631371.75719634.319357.9418
9679.969357.71849828.596 321.092 9897.94329.47759956.006269.483310003.59261.1856
10132.72289.095910355.64284.947210428.46295.0762   10490287.028410539.57297.3828
10719.02 294.40910766.56301.282510855.19 295.31911443.65306.173411512.28301.9109
#Mann= 3 , 0 , 0
8487.633    0.12       08487.633    0.12       011512.28    0.12       0
#XS Ineff= 2 , 0
       0                10135.59       0
Bank Sta=8487.633,11512.28
Exp/Cntr=0.3,0.1

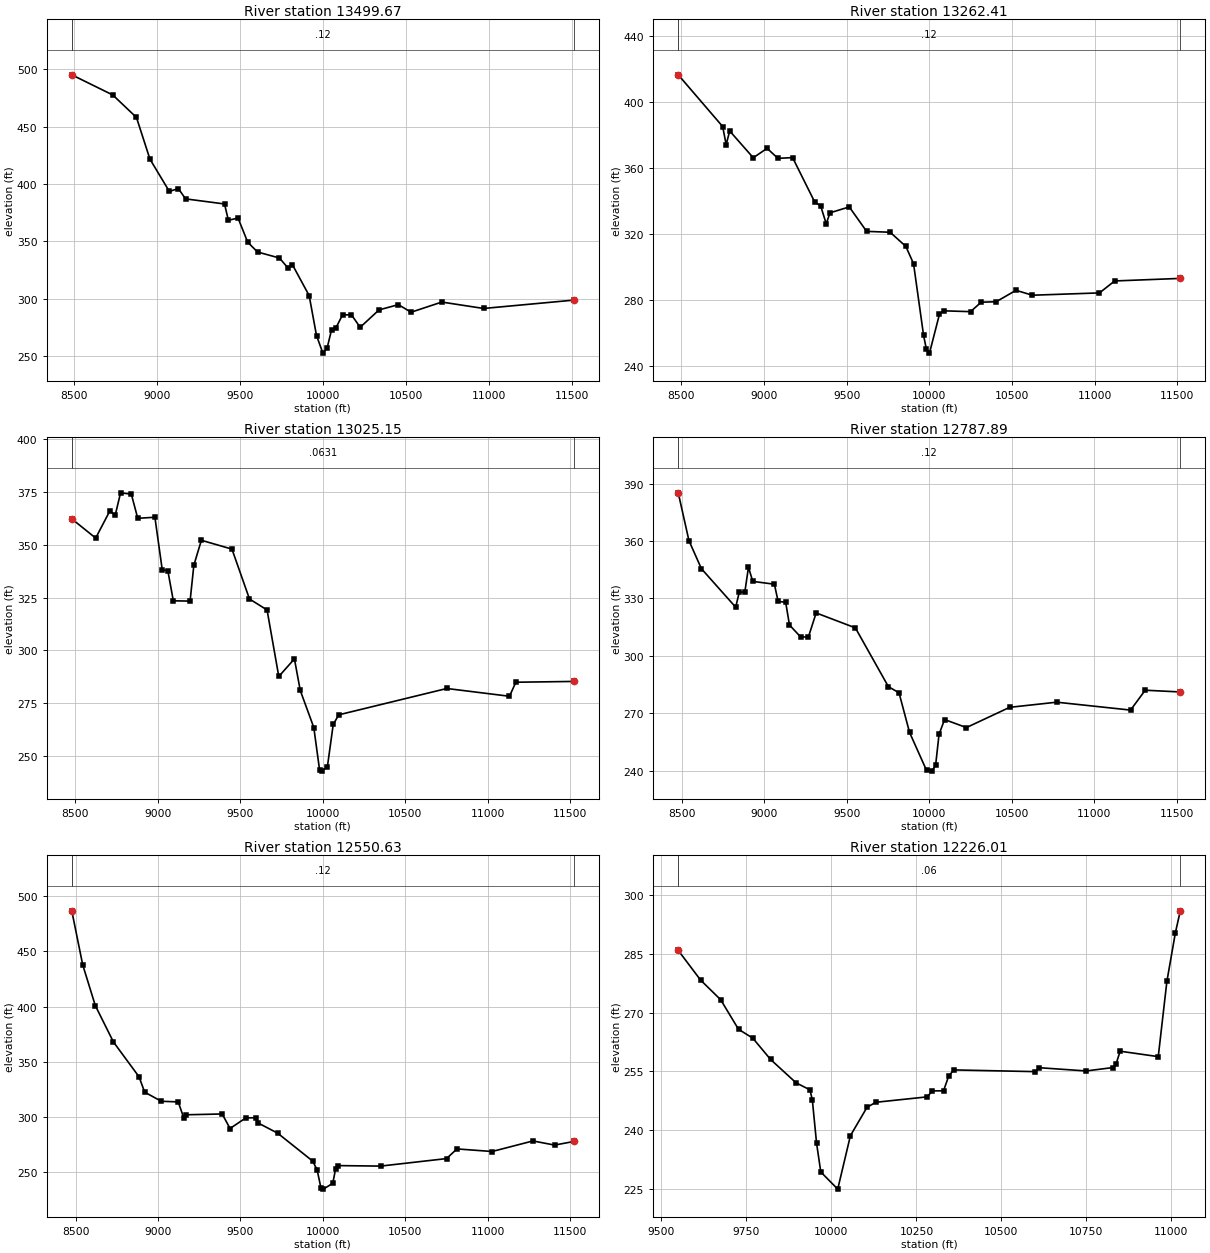
Type RM Length L Ch R = 1 ,13499.67,237.259200,237.259200,237.259200
XS GIS Cut Line= 6
554979.294445887 742344.05659228554350.848642492742153.246513394
553867.370042614741882.036688842553518.360349462741612.206706209
552930.665491688741019.987299201552516.848649265740676.492833395
#Sta/Elev= 30
8486.465495.09188733.848477.52428876.515457.95838957.681421.65829074.925393.4726
9128.879396.05699172.448387.0368 9407.36382.58999430.681368.37979488.972370.3152
9547.263349.27359606.552340.75229738.829335.4904 9787.58327.2395 9816.65329.7214
9917.805302.75099961.989267.970410000.41252.6519 10026.5257.365610052.91273.0777
10079.32274.726310118.93 285.96810172.65286.025610225.38275.146510338.93290.3151
10455.44294.872910532.38288.288110717.27297.137610969.47291.561811513.54 298.832
#Mann= 3 , 0 , 0
8486.465    0.12       08486.465    0.12       011513.54    0.12       0
#XS Ineff= 2 , 0
       0                10173.22       0
Bank Sta=8486.465,11513.54
Exp/Cntr=0.3,0.1

Type RM Length L Ch R = 1 ,13262.41,237.259200,237.259200,237.259200
XS GIS Cut Line= 6
555120.739830746742183.154860368554501.691295462741950.928071846
553781.274925494741523.182862954 553525.95290589741333.937988849
552930.869961651740797.851273106552604.541748847740537.213165382
#Sta/Elev= 30
 8481.45416.54158750.111385.18468771.421374.20938792.731382.48368935.281366.2454
9018.851371.9581 9084.56365.88639173.277366.33529308.124339.1677 9342.41337.1977
9376.695326.19119399.552332.85189516.005336.42699621.072321.58769762.981321.0728
9858.268312.47699904.836302.00799965.465258.58939981.813250.423210001.28247.7483
 10061.6271.360910086.15273.412110249.43272.898910314.37278.642910404.57278.9103
10524.53285.846310623.52 282.87211029.62284.275111121.44291.520311518.53  293.07
#Mann= 3 , 0 , 0
 8481.45    0.12       0 8481.45    0.12       011518.53    0.12       0
#XS Ineff= 2 , 0
       0                 10108.5       0
Bank Sta=8481.45,11518.53
Exp/Cntr=0.3,0.1

Type RM Length L Ch R = 1 ,13025.15,237.259200,237.259200,237.259200
XS GIS Cut Line= 6
555241.090579328 742021.80501373554886.274636663741882.653697428
554631.047394812 741759.98150719553816.695010608741265.070352622
553581.278396866741091.759363854552707.437310874740372.480720751
#Sta/Elev= 30
8478.927362.19248623.819353.09848709.819365.96858742.069363.88278774.616374.4954
8839.796373.88238878.642362.45938982.663362.94069027.314337.97499060.802337.7661
9094.291323.43799195.808323.30219218.591340.25129264.156352.06079449.468347.8855
9555.675324.31169662.233319.11049733.271287.65749827.989295.98359863.338281.0659
9945.448263.54019980.638243.33569992.368242.912910027.71244.944310063.13264.9825
10096.68269.532910751.31281.984511131.16278.307711169.58284.940911521.07285.3235
#Mann= 3 , 0 , 0
8478.927  0.0631       08478.927  0.0631       011521.07  0.0631       0
#XS Ineff= 2 , 0
       0                               0
Bank Sta=8478.927,11521.07
Exp/Cntr=0.3,0.1

Type RM Length L Ch R = 1 ,12787.89,237.259200,237.259200,237.259200
XS GIS Cut Line= 6
555325.156718021741886.695012576554779.916900633741637.430580678
554331.428875763741362.137096941 554118.71731399741200.626267867
553378.027389381 740567.74511205552844.286715529740153.909056032
#Sta/Elev= 30
8478.286385.14448543.219360.17938618.777345.52758826.553325.43428848.639333.4115
8881.769 333.2378904.062346.28938929.975338.91849061.138337.42929083.787328.4723
  9129.6327.99869152.507316.14939221.227 309.8229267.592309.93759314.274 322.445
9552.034314.65089752.329283.94629816.595280.76969880.416260.0846  9983.6240.1994
10015.16239.8629 10038.3242.822910059.31259.099510092.83266.7943 10225.1262.5993
10487.28273.167910772.51275.8501 11220.2271.729211308.94 282.09811521.75281.1939
#Mann= 3 , 0 , 0
8478.286    0.12       08478.286    0.12       011521.75    0.12       0
#XS Ineff= 2 , 0
       0                               0
Bank Sta=8478.286,11521.75
Exp/Cntr=0.3,0.1

Type RM Length L Ch R = 1 ,12550.63,324.622600,324.622600,324.622600
XS GIS Cut Line= 6
 555495.74482692741741.836399069554971.990651496741492.143246088
554509.680468028741209.688042181  554315.0357744741060.586350387
553844.249295172740649.193696576553010.759044336740007.186301926
#Sta/Elev= 30
8477.373486.73158543.596437.88658620.087400.87798729.934367.92778885.591 336.308
8919.356322.43489020.653314.15229123.094313.60499157.462 298.7559168.918301.9174
9389.887 302.6629437.224 289.4729533.128299.11929593.434299.23839605.647294.6513
9726.404285.24129938.492259.97069965.628251.97029988.524235.694710003.33 234.556
10060.55239.848910077.39252.7901 10092.2255.874210350.46255.427710750.33262.2248
10813.75270.9883 11027.1268.651311274.71 278.22711405.71274.465811522.65 277.736
#Mann= 3 , 0 , 0
8477.373    0.12       08477.373    0.12       011522.65    0.12       0
#XS Ineff= 2 , 0
       0                               0
Bank Sta=8477.373,11522.65
Exp/Cntr=0.3,0.1

Type RM Length L Ch R = 1 ,12226.01,110.828800,110.828800,110.828800
XS GIS Cut Line= 6
554544.843433249741104.019075557554464.406338632740848.661837161
554432.630745977740764.411383659554235.774108618 740496.98349905
554144.774342328740396.698042303553623.368765091740006.098045362
#Sta/Elev= 30
9549.457285.90129615.143 278.325 9674.31273.2922 9726.76265.73999768.721263.4829
9821.112258.02949895.926252.07319936.841250.26629943.858247.71079956.308236.6427
9968.758229.281310018.56224.8944 10055.9 238.56310104.72245.797910130.48247.0878
 10282.5248.479710296.01249.993910329.75250.020610344.64253.707910359.52255.3614
10599.36254.920710611.85255.920210749.29255.0964 10827.9255.959410836.76256.7605
10849.25260.140310961.33258.7536 10986.7277.960311011.69290.405211026.22296.0166
#Mann= 3 , 0 , 0
9549.457    0.06       09549.457    0.06       011026.22    0.06       0
#XS Ineff= 2 , 0
       0                               0
Bank Sta=9549.457,11026.22
Exp/Cntr=0.3,0.1