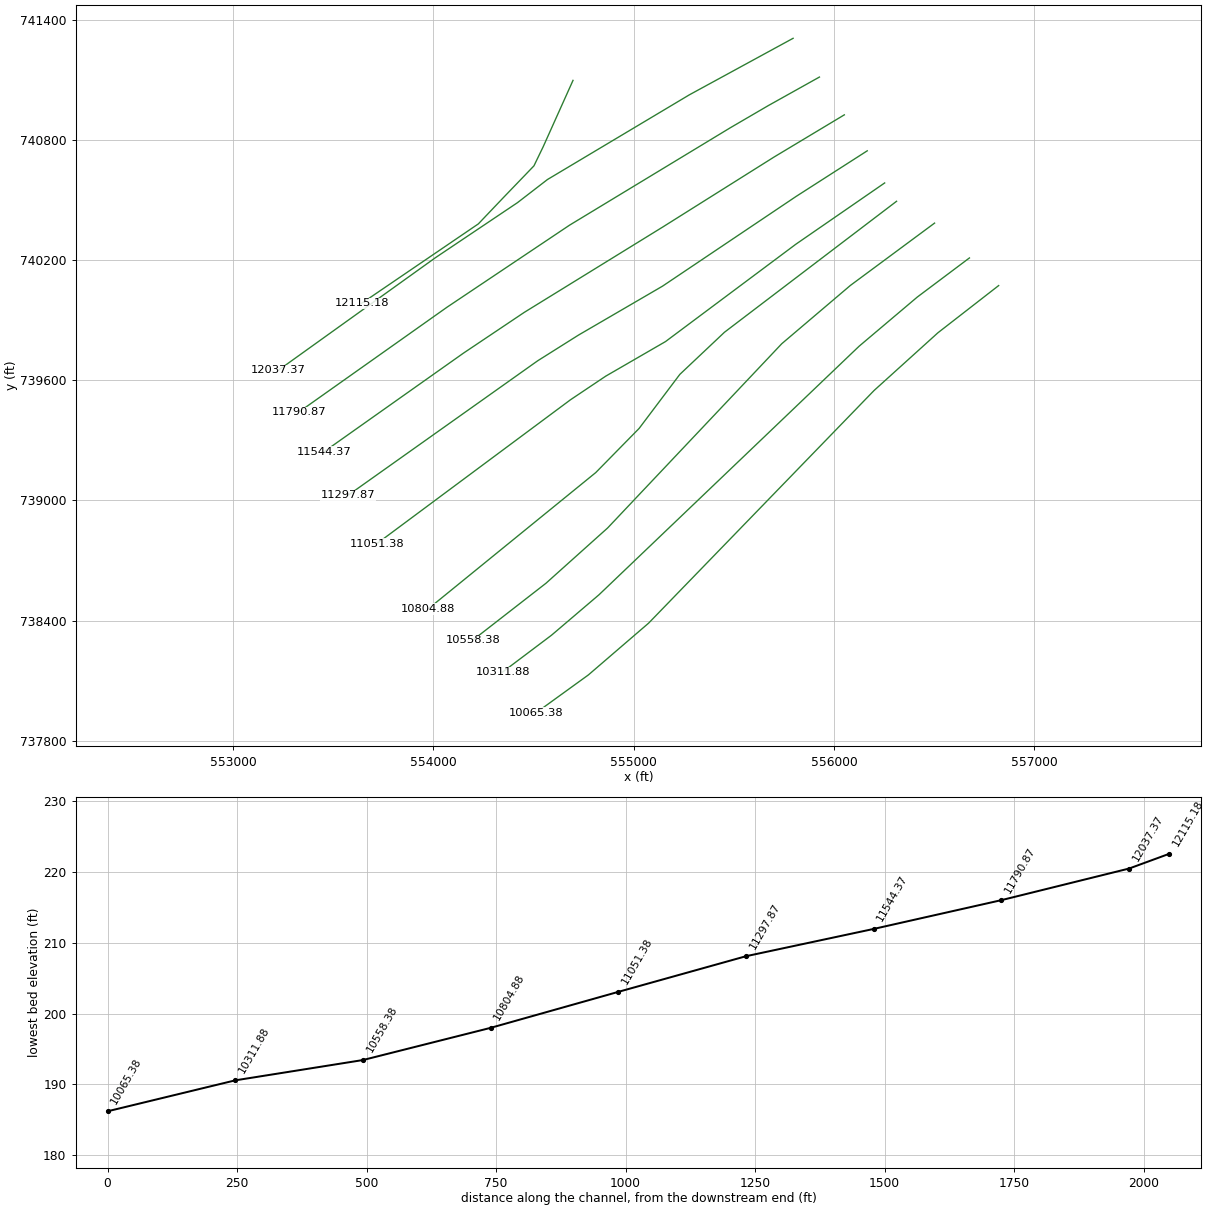
HEC-RAS study 1761_ras.prj: 1761

--- 1761_ras.g01 (geometry) --- (continued)

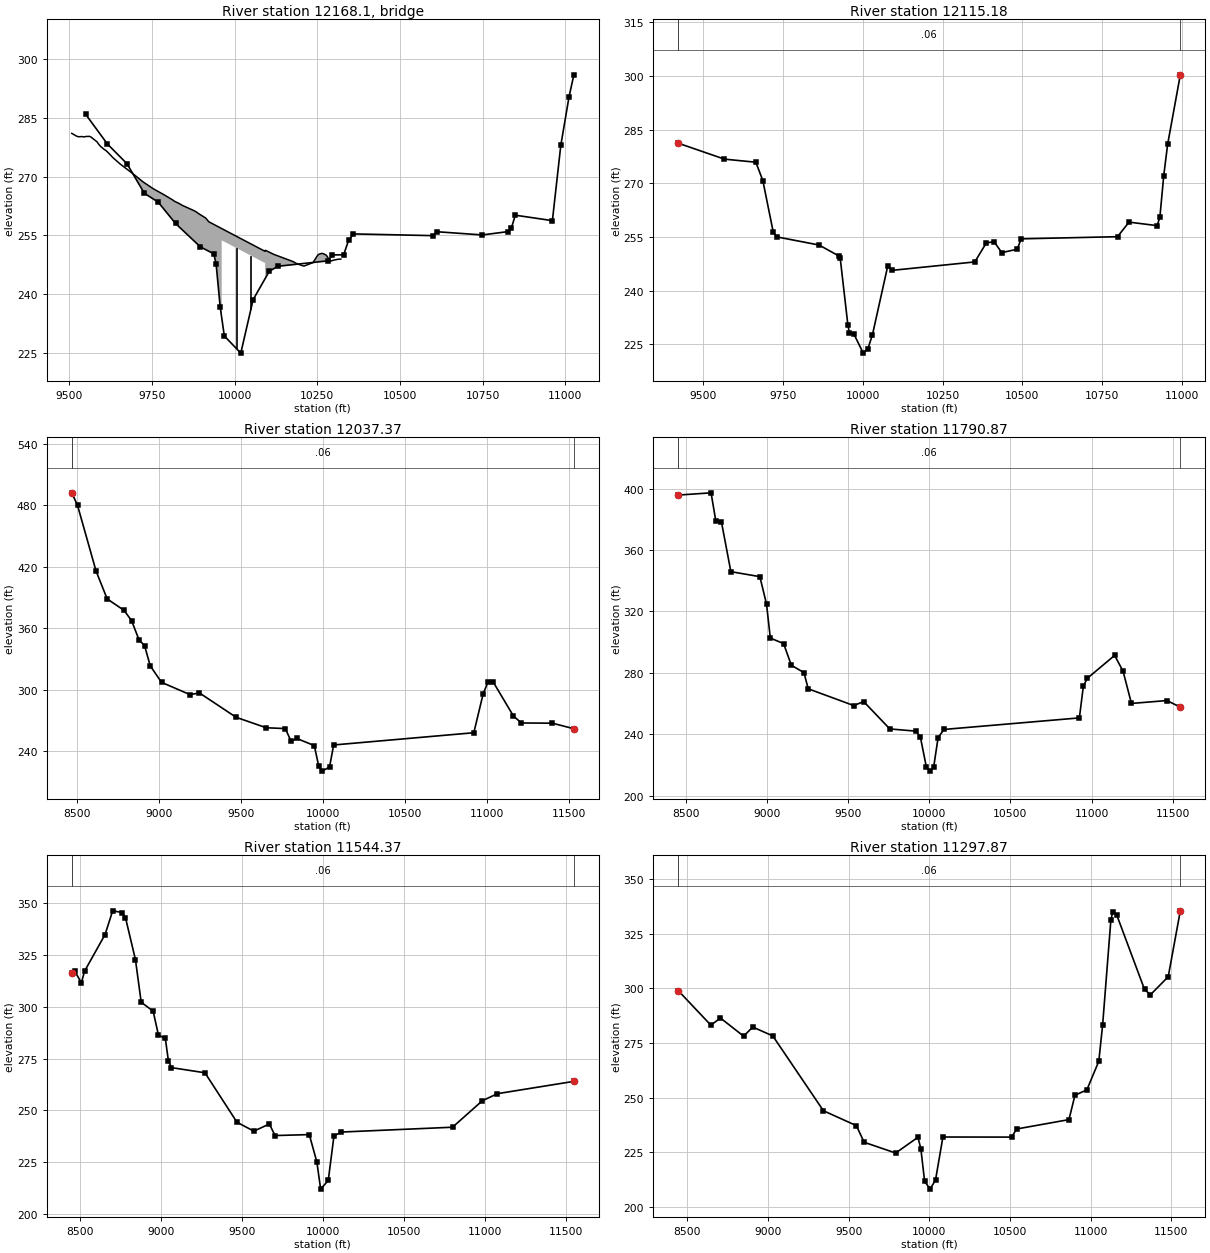
Type RM Length L Ch R = 3 , 12168.1,,,
BEGIN DESCRIPTION:
END DESCRIPTION:
Bridge Culvert--1,0,-1,-1, 0
Deck Dist Width WeirC Skew NumUp NumDn MinLoCord MaxHiCord MaxSubmerge Is_Ogee
38.518100,33.792600,2.6,0, 51, 51, , , 0.95, 0, 0,0,,
 9507.21 9521.83 9527.51 9538.73 9543.86 9549.96 9561.18 9565.89 9583.63 9587.92
 9594.85 9606.07 9609.95 9617.29 9631.98 9654.01 9693.46 9723.45 9754.13 9784.81
 9812.00 9817.88 9834.10 9840.31 9878.30 9885.17 9887.95 9912.39 9921.68 9960.83
 9960.8310091.4710092.3910092.3910092.8610118.8610178.2610183.8610193.9110209.46
10236.9610250.4710254.1010263.9710268.9810277.4810283.8610290.9810298.7310313.61
10321.18
  281.06  280.34  280.19  280.24  280.14  280.26  280.29  280.08  278.89  278.36
  277.67  276.90  276.71  276.14  274.83  273.20  270.66  268.62  266.89  265.44
  264.07  263.71  263.04  262.71  261.25  260.92  260.71  259.42  258.47  256.73
  256.73  250.93  251.09  251.09  251.17  250.12  248.24  247.93  247.57  247.13
  248.03  249.82  250.15  250.40  250.28  249.91  249.07  248.41  248.65  248.89
  248.92
 -718.94 -719.66 -719.81 -719.76 -719.86 -719.74 -719.71 -719.92 -721.11 -721.64
 -722.33 -723.10 -723.29 -723.86 -725.17 -726.80 -729.34 -731.38 -733.11 -734.56
 -735.93 -736.29 -736.96 -737.29 -738.75 -739.08 -739.29 -740.58 -741.53 -743.27
  253.73  247.93  248.09 -748.91 -748.83 -749.88 -751.76 -752.07 -752.43 -752.87
 -751.97 -750.18 -749.85 -749.60 -749.72 -750.09 -750.93 -751.59 -751.35 -751.11
 -751.08
 9507.21 9521.83 9527.51 9538.73 9543.86 9549.96 9561.18 9565.89 9583.63 9587.92
 9594.85 9606.07 9609.95 9617.29 9631.98 9654.01 9693.46 9723.45 9754.13 9784.81
 9812.00 9817.88 9834.10 9840.31 9878.30 9885.17 9887.95 9912.39 9921.68 9930.59
 9930.5910062.1510062.1510091.4710092.8610118.8610178.2610183.8610193.9110209.46
10236.9610250.4710254.1010263.9710268.9810277.4810283.8610290.9810298.7310313.61
10321.18
  281.06  280.34  280.19  280.24  280.14  280.26  280.29  280.08  278.89  278.36
  277.67  276.90  276.71  276.14  274.83  273.20  270.66  268.62  266.89  265.44
  264.07  263.71  263.04  262.71  261.25  260.92  260.71  259.42  258.47  258.07
  258.07  252.23  252.23  250.93  251.17  250.12  248.24  247.93  247.57  247.13
  248.03  249.82  250.15  250.40  250.28  249.91  249.07  248.41  248.65  248.89
  248.92
 -718.94 -719.66 -719.81 -719.76 -719.86 -719.74 -719.71 -719.92 -721.11 -721.64
 -722.33 -723.10 -723.29 -723.86 -725.17 -726.80 -729.34 -731.38 -733.11 -734.56
 -735.93 -736.29 -736.96 -737.29 -738.75 -739.08 -739.29 -740.58 -741.53 -741.93
  255.07  249.23 -747.77 -749.07 -748.83 -749.88 -751.76 -752.07 -752.43 -752.87
 -751.97 -750.18 -749.85 -749.60 -749.72 -750.09 -750.93 -751.59 -751.35 -751.11
 -751.08
Pier Skew, UpSta & Num, DnSta & Num=  ,10004.19, 2 ,9973.95, 2 , 0 , 0 , 0 ,,
    3.00    3.00
 -745.20  254.80
    3.00    3.00
 -743.85  256.15
Pier Skew, UpSta & Num, DnSta & Num=  ,10049.04, 2 ,10018.80, 2 , 0 , 0 , 0 ,,
    3.00    3.00
 -747.19  252.81
    3.00    3.00
 -745.84  254.16
BR Coef=-1 , 0 , 0 ,, 0 ,,,0.8,0,1,0,
WSPro=,,,, 1 ,,,, 0 ,,,, 0 ,,,,-1 ,-1 ,-1 , 0 , 0 , 0 , 0 , 0
BC Design=,, 0 ,, 0 ,,,,,,

Type RM Length L Ch R = 1 ,12115.18,77.807800,77.807800,77.807800
XS GIS Cut Line= 6
554697.033526152741097.030178726554547.632037759740764.688092262
554501.896888256740670.168783277554346.397379905740508.571254998
554224.436981201740380.512836352553642.076077402739984.141540572
#Sta/Elev= 30
9420.864281.25089565.622276.79199664.298275.92699686.226270.79829719.118256.2966
9730.082255.04989862.661252.77849925.175249.69299929.037249.05499952.931230.4838
9957.882228.15739972.304227.821410001.15  222.5510015.57223.729610029.99 227.648
10077.83246.823510091.71245.693710351.15248.051510387.44253.398410411.64253.6823
10435.83250.650110484.21251.601410496.65254.506110798.78255.106110835.01259.1807
10923.19258.192810931.79260.621910943.88272.210310955.98280.896510995.81300.3636
#Mann= 3 , 0 , 0
9420.864    0.06       09420.864    0.06       010995.81    0.06       0
#XS Ineff= 2 , 0
       0                               0
Bank Sta=9420.864,10995.81
Exp/Cntr=0.3,0.1

Type RM Length L Ch R = 1 ,12037.37,246.499200,246.499200,246.499200
XS GIS Cut Line= 6
555795.967042895741307.083163221555278.380691623741025.092772786
554569.477547342 740601.96046234554419.720453188740486.429297023
554009.772278852740211.409277162553225.253931104739649.094129966
#Sta/Elev= 30
8468.348 492.2678503.354480.07318616.396415.95518684.222388.67188786.525377.5784
8833.127367.51718878.248348.84188912.644342.97158947.039323.32739015.831 307.193
9189.392295.19989247.416296.8164 9471.16273.03379654.649262.82619771.214 262.015
9806.439249.64719841.683252.35249948.091245.38139975.444225.10499995.447220.4624
10041.08224.474310066.16245.9989 10921.4257.963610978.16295.837211006.79307.2004
11039.84307.4706 11163.2 274.25711211.73 267.49511400.74  267.2911531.69261.8558
#Mann= 3 , 0 , 0
8468.348    0.06       08468.348    0.06       011531.69    0.06       0
#XS Ineff= 2 , 0
       0                               0
Bank Sta=8468.348,11531.69
Exp/Cntr=0.3,0.1

Type RM Length L Ch R = 1 ,11790.87,246.499200,246.499200,246.499200
XS GIS Cut Line= 6
555927.406375318741113.611650656555671.637107864740970.783424344
555483.823919331740861.241622949554680.068903254740374.244909186
 554067.83056196739964.330037264553327.905934866 739440.71170025
#Sta/Elev= 30
8453.288395.78118655.545397.24088685.115378.69868719.476378.29718777.563345.8942
8956.199342.65398997.307324.75079020.654302.65549102.368299.05339150.206284.9558
9227.738280.16689254.123269.62079534.287258.72829596.018261.28279756.773243.4921
9920.026242.01589945.697237.92969981.839218.795210005.99216.004810027.24218.7568
10054.45237.857810090.79243.150810924.83250.672410949.36271.322610973.89276.4713
   11142291.367211193.83281.111311245.65260.088411464.44261.961611546.73257.6719
#Mann= 3 , 0 , 0
8453.288    0.06       08453.288    0.06       011546.73    0.06       0
#XS Ineff= 2 , 0
       0                               0
Bank Sta=8453.288,11546.73
Exp/Cntr=0.3,0.1

Type RM Length L Ch R = 1 ,11544.37,246.499200,246.499200,246.499200
XS GIS Cut Line= 6
556051.732362993740924.921621544555701.752489817740714.784582119
555146.716441177  740365.8195797554453.835618637739938.765352012
554149.856871188739734.960680065553454.268506049739243.104050846
#Sta/Elev= 30
8452.144316.32718471.724317.08568511.194311.5498 8530.93317.16528657.474334.8903
8704.321346.32318763.906345.51248783.117 343.0888844.861322.72618880.165302.1947
 8953.91297.86148986.475286.3128 9029.06284.68339047.848 273.9299066.636270.6131
  9273.3268.12389470.778244.24039574.727239.93769670.003243.38069705.979237.8141
9916.643238.2703 9963.41225.01169986.793211.944710033.59216.1423 10068.7 237.576
10112.39 239.50110799.86241.838610983.57254.618411076.91258.040511547.85263.9754
#Mann= 3 , 0 , 0
8452.144    0.06       08452.144    0.06       011547.85    0.06       0
#XS Ineff= 2 , 0
       0                               0
Bank Sta=8452.144,11547.85
Exp/Cntr=0.3,0.1

Type RM Length L Ch R = 1 ,11297.87,246.499200,246.499200,246.499200
XS GIS Cut Line= 6
556166.207847268740745.298352592555812.095438275 740518.25631337
555143.875432864740069.454785998554724.253040581739825.098011945
554520.209645639739696.607175502553573.706970466 739025.12532189
#Sta/Elev= 30
8443.479298.92218645.696283.12898705.492286.37458848.731278.08738905.617282.2499
9029.721278.20129343.737 243.9539548.224 237.139 9596.04229.53749791.464224.6073
9929.655231.80839947.754226.60169970.895211.802210004.54208.094710038.64212.2268
10084.53231.943310510.72231.898310541.68235.611210866.16239.899710903.15251.0346
10977.14253.521911051.13266.603111074.75283.123811126.02 331.29811137.44334.8687
 11162.1333.586511334.74299.4395 11371.5297.046311481.56305.283111556.52335.4335
#Mann= 3 , 0 , 0
8443.479    0.06       08443.479    0.06       011556.52    0.06       0
#XS Ineff= 2 , 0
       0                               0
Bank Sta=8443.479,11556.52
Exp/Cntr=0.3,0.1

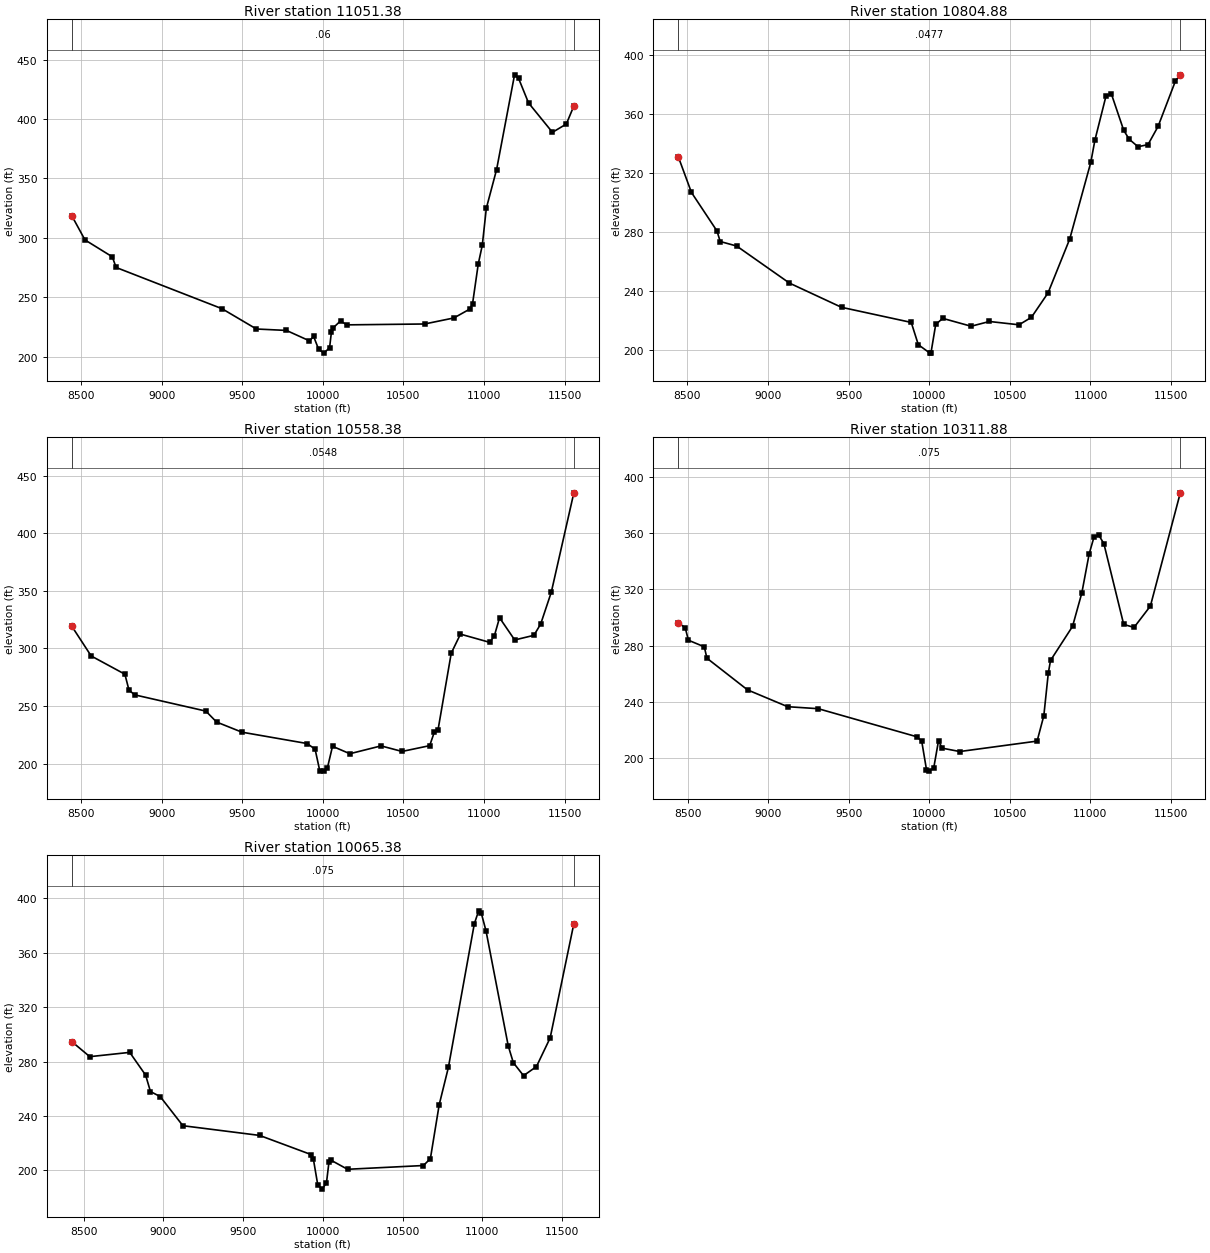
Type RM Length L Ch R = 1 ,11051.38,246.499200,246.499200,246.499200
XS GIS Cut Line= 6
556253.173619017740584.894553298555809.527041297740278.774172658
555158.988543096739792.865671769554860.416473622739620.149081076
554684.445866568739502.236824656553716.747058442738783.095149454
#Sta/Elev= 30
8443.099318.67248525.051298.30148694.412284.10028718.018275.13179374.718240.4437
9588.124223.36359774.446222.16049917.136213.40649943.067217.06779973.952  206.37
10006.37203.066110041.97207.614310053.29220.600110064.62 224.35710109.79230.1681
10148.82226.845410631.42227.580710813.14232.663910912.01240.169910928.51 244.413
10963.97277.961710989.11293.842711014.15324.948311077.85357.526611189.16437.1891
11214.06434.245911275.88413.561811424.25388.814211510.17395.792511556.91 410.946
#Mann= 3 , 0 , 0
8443.099    0.06       08443.099    0.06       011556.91    0.06       0
#XS Ineff= 2 , 0
       0                               0
Bank Sta=8443.099,11556.91
Exp/Cntr=0.3,0.1

Type RM Length L Ch R = 1 ,10804.88,246.499200,246.499200,246.499200
XS GIS Cut Line= 6
556312.601168002740493.352160675555453.462793638739839.526072247
555230.344612376739628.938443961555027.196165382739359.242164644
554810.625123607739138.749758956553973.149304866738457.474683029
#Sta/Elev= 30
8442.583331.09648524.451306.82598682.907280.73328702.963273.59078805.216270.5266
9132.793245.40799455.524229.02739888.127218.78059931.928203.715610003.78197.9891
10010.71198.283610039.94 217.411 10083.5221.539110259.48216.200510373.14219.4201
10556.67 217.178 10633.7222.242510736.68238.748710871.35275.286711001.93327.1549
11027.89342.393911096.05371.990711129.99373.473411206.57348.800511241.03342.8064
11294.92337.788411356.84339.2084 11419.4351.527311527.49382.398811557.41 386.486
#Mann= 3 , 0 , 0
8442.583  0.0477       08442.583  0.0477       011557.41  0.0477       0
#XS Ineff= 2 , 0
       0                10068.61       0
Bank Sta=8442.583,11557.41
Exp/Cntr=0.3,0.1

Type RM Length L Ch R = 1 ,10558.38,246.499200,246.499200,246.499200
XS GIS Cut Line= 6
556502.367064475740384.381404727556082.053857753 740073.17660658
555739.515741552739782.220123684554869.855015623738862.109377909
554561.891064989738585.990047857554196.694681457738301.995778148
#Sta/Elev= 30
8442.015319.25728562.501293.42148771.633277.58898796.932263.86778831.493259.6929
9274.257245.56089340.648236.07729498.085227.25759902.356217.40569952.037212.5259
9981.433193.547210007.74193.447910028.98196.505710060.26215.003710167.88208.5489
10361.53215.362210491.73210.530410663.23215.562210692.07227.269310715.41229.5079
10797.05295.847610854.27  312.3811035.69305.236311064.68310.902211096.81326.5966
11191.01307.318511310.16311.343311352.02321.1127   11418348.7574   11558435.0446
#Mann= 3 , 0 , 0
8442.015  0.0548       08442.015  0.0548       0   11558  0.0548       0
#XS Ineff= 2 , 0
       0                10062.43       0
Bank Sta=8442.015,11558
Exp/Cntr=0.3,0.1

Type RM Length L Ch R = 1 ,10311.88,246.499200,246.499200,246.499200
XS GIS Cut Line= 6
556676.443236854740210.445161249 556415.84095095740014.892631921
556125.325396006739769.404396102 554826.96056832738528.751357323
554589.817836422738326.755414537554345.117450172738142.473319084
#Sta/Elev= 30
8439.867296.39818483.611292.58138503.111283.83768601.615279.14798618.316271.0143
8870.357248.4752 9119.99236.47769309.864235.05869923.131215.05079952.898212.0008
9982.665191.64829997.549190.583510027.51192.733310057.48212.261710079.78206.9589
10189.29204.542210670.14211.974910711.87230.052210739.69260.3969 10753.6269.4474
10890.39293.697810947.94317.445210993.64345.324411024.35357.592911054.58358.4565
11085.05352.639711208.25295.114611272.58292.9519 11374.2308.177511560.13 388.833
#Mann= 3 , 0 , 0
8439.867   0.075       08439.867   0.075       011560.13   0.075       0
#XS Ineff= 2 , 0
       0                10060.17       0
Bank Sta=8439.867,11560.13
Exp/Cntr=0.3,0.1

Type RM Length L Ch R = 1 ,10065.38,95.023300,95.023300,95.023300
XS GIS Cut Line= 6
556822.329237855740072.418404407556519.131321752739836.801719821
556200.174747678739548.447017857 555074.73699813738387.123368145
554773.719234735738128.297026164554513.667899883737940.114294358
#Sta/Elev= 30
8425.172294.70858538.223283.62758788.721286.77978888.328 270.0758918.867 257.968
8979.945254.28019122.305232.85099603.258225.72119927.387211.59649941.071208.1549
9968.437 189.2859995.804186.218310022.98190.836610038.54206.088910050.22207.5657
10155.11200.8094 10631.1203.572710674.88208.618710730.12 248.27910787.72275.6766
10950.63381.385410977.58390.8699 10994.1389.241211023.93376.075511163.37291.5132
11195.25279.201211259.21269.663111340.11276.324111426.24297.429311574.84381.4096
#Mann= 3 , 0 , 0
8425.172   0.075       08425.172   0.075       011574.84   0.075       0
#XS Ineff= 2 , 0
       0                10050.89       0
Bank Sta=8425.172,11574.84
Exp/Cntr=0.3,0.1