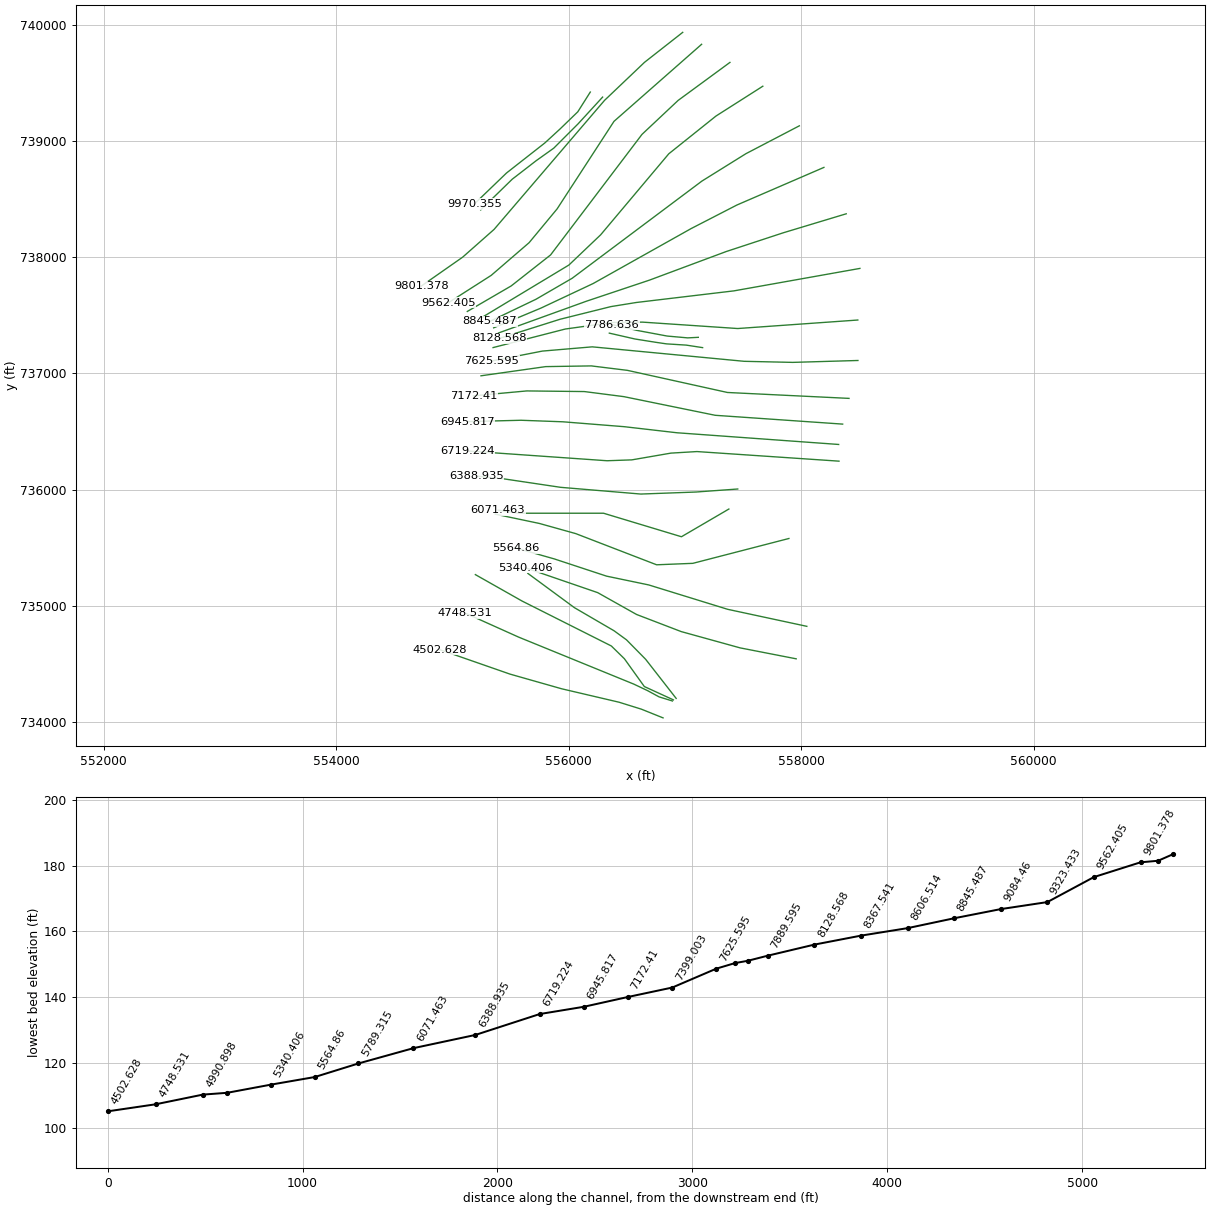
HEC-RAS study 1761_ras.prj: 1761

--- 1761_ras.g01 (geometry) --- (continued)

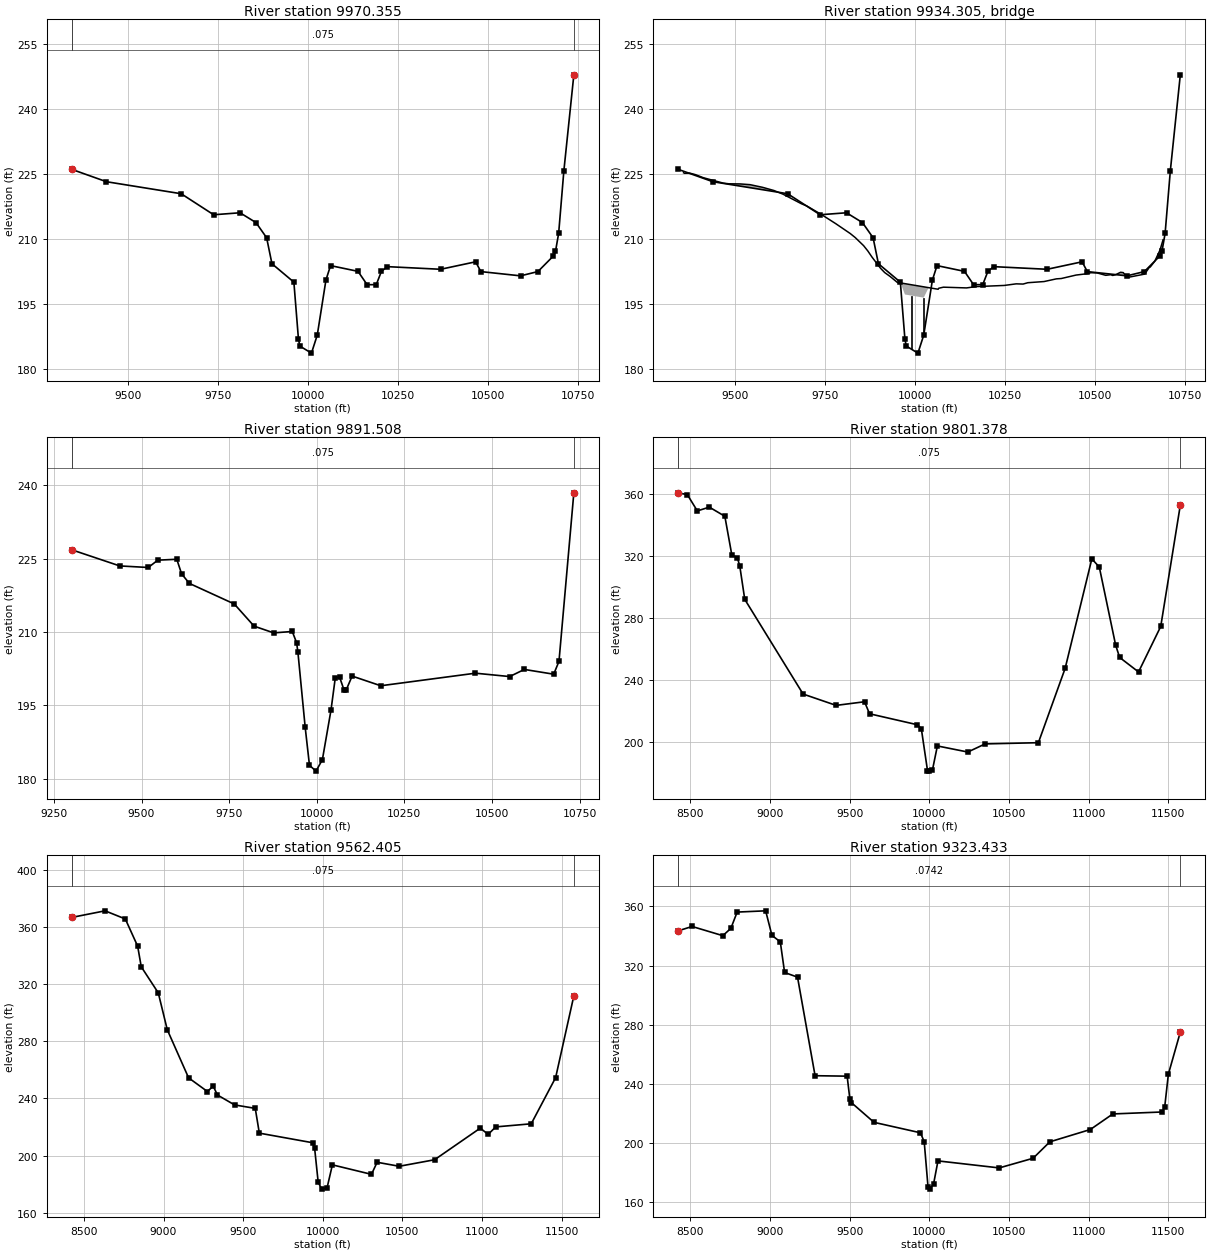
Type RM Length L Ch R = 1 ,9970.355,78.846600,78.846600,78.846600
XS GIS Cut Line= 6
556186.524475873739419.280006796556078.885587007739249.141117916
555924.371698081739099.835562348555795.899475873738981.780006796
555466.038364738738723.099451229555188.260586977738455.738340124
#Sta/Elev= 30
 9342.83226.05599439.202223.20119646.903220.42539737.201215.56879810.508216.0283
9854.846213.75779884.404210.25649899.183204.25249960.128200.00019972.869186.8089
9976.719185.2355   10009183.605710025.13187.767810049.31200.518510062.05 203.821
10138.34202.495810163.72 199.41310189.09 199.42210203.36 202.47310219.61203.5833
10368.02202.974210465.32204.701910479.74202.438910590.09201.458810638.36202.4435
10681.62206.071210687.25207.115510696.04211.298610710.46225.691910738.24247.8923
#Mann= 3 , 0 , 0
 9342.83   0.075       0 9342.83   0.075       010738.24   0.075       0
#XS Ineff= 2 , 0
       0                10061.42       0
Bank Sta=9342.83,10738.24
Exp/Cntr=0.3,0.1

Type RM Length L Ch R = 3 ,9934.305,,,
BEGIN DESCRIPTION:
END DESCRIPTION:
Bridge Culvert--1,0,-1,-1, 0
Deck Dist Width WeirC Skew NumUp NumDn MinLoCord MaxHiCord MaxSubmerge Is_Ogee
26.464000,25.918600,2.6,0, 60, 60, , , 0.95, 0, 0,0,,
 9357.57 9360.40 9374.52 9390.14 9412.47 9468.24 9483.86 9515.10 9542.64 9577.58
 9608.83 9633.89 9684.95 9700.03 9740.72 9780.78 9820.74 9834.63 9858.03 9869.73
 9881.44 9904.84 9916.54 9932.11 9951.62 9960.17 9960.1710057.2910057.2910065.25
10066.6410079.8910144.1010170.2910248.8610282.1310301.2510314.3410359.5710393.73
10407.4510448.6110477.3410489.7710506.5610530.9310544.6510550.3710558.3710572.09
10579.5810585.8110594.1910638.0010640.6910652.6110654.4110667.2210681.8210690.31
  225.27  225.15  225.19  224.85  224.13  222.87  222.72  222.69  222.52  221.90
  221.17  220.33  218.12  217.60  215.63  213.50  211.24  210.31  208.43  207.21
  205.78  203.23  202.22  201.29  199.95  199.83  199.83  198.47  198.47  198.36
  198.59  198.84  198.67  198.97  199.24  199.61  199.56  199.87  200.14  200.76
  200.84  201.64  201.93  202.18  202.14  201.58  201.72  201.55  201.72  202.28
  202.21  201.59  201.13  201.84  202.05  203.48  203.47  204.82  207.43  209.79
 -774.73 -774.85 -774.81 -775.15 -775.87 -777.13 -777.28 -777.31 -777.48 -778.10
 -778.83 -779.67 -781.88 -782.40 -784.37 -786.50 -788.76 -789.69 -791.57 -792.79
 -794.22 -796.77 -797.78 -798.71 -800.05 -800.17  197.33  195.97 -801.53 -801.64
 -801.41 -801.16 -801.33 -801.03 -800.76 -800.39 -800.44 -800.13 -799.86 -799.24
 -799.16 -798.36 -798.07 -797.82 -797.86 -798.42 -798.28 -798.45 -798.28 -797.72
 -797.79 -798.41 -798.87 -798.16 -797.95 -796.52 -796.53 -795.18 -792.57 -790.21
 9357.57 9360.40 9374.52 9390.14 9412.47 9468.24 9483.86 9515.10 9542.64 9577.58
 9608.83 9633.89 9684.95 9700.03 9740.72 9780.78 9820.74 9834.63 9858.03 9869.73
 9881.44 9904.84 9916.54 9932.11 9951.62 9962.72 9962.7210059.8310059.8310065.25
10066.6410079.8910144.1010170.2910248.8610282.1310301.2510314.3410359.5710393.73
10407.4510448.6110477.3410489.7710506.5610530.9310544.6510550.3710558.3710572.09
10579.5810585.8110594.1910638.0010640.6910652.6110654.4110667.2210681.8210690.31
  225.27  225.15  225.19  224.85  224.13  222.87  222.72  222.69  222.52  221.90
  221.17  220.33  218.12  217.60  215.63  213.50  211.24  210.31  208.43  207.21
  205.78  203.23  202.22  201.29  199.95  199.80  199.80  198.43  198.43  198.36
  198.59  198.84  198.67  198.97  199.24  199.61  199.56  199.87  200.14  200.76
  200.84  201.64  201.93  202.18  202.14  201.58  201.72  201.55  201.72  202.28
  202.21  201.59  201.13  201.84  202.05  203.48  203.47  204.82  207.43  209.79
 -774.73 -774.85 -774.81 -775.15 -775.87 -777.13 -777.28 -777.31 -777.48 -778.10
 -778.83 -779.67 -781.88 -782.40 -784.37 -786.50 -788.76 -789.69 -791.57 -792.79
 -794.22 -796.77 -797.78 -798.71 -800.05 -800.20  197.30  195.93 -801.57 -801.64
 -801.41 -801.16 -801.33 -801.03 -800.76 -800.39 -800.44 -800.13 -799.86 -799.24
 -799.16 -798.36 -798.07 -797.82 -797.86 -798.42 -798.28 -798.45 -798.28 -797.72
 -797.79 -798.41 -798.87 -798.16 -797.95 -796.52 -796.53 -795.18 -792.57 -790.21
Pier Skew, UpSta & Num, DnSta & Num=  ,9992.04, 2 ,9994.59, 2 , 0 , 0 , 0 ,,
    3.00    3.00
 -800.61  199.39
    3.00    3.00
 -800.65  199.35
Pier Skew, UpSta & Num, DnSta & Num=  ,10025.42, 2 ,10027.96, 2 , 0 , 0 , 0 ,,
    3.00    3.00
 -801.08  198.92
    3.00    3.00
 -801.12  198.88
BR Coef=-1 , 0 , 0 ,, 0 ,,,0.8,0,1,0,
WSPro=,,,, 1 ,,,, 0 ,,,, 0 ,,,,-1 ,-1 ,-1 , 0 , 0 , 0 , 0 , 0
BC Design=,, 0 ,, 0 ,,,,,,

Type RM Length L Ch R = 1 ,9891.508,90.130100,90.130100,90.130100
XS GIS Cut Line= 6
556292.427253664739375.877229005556080.621698081739144.974451229
555872.288364768738936.641117901555721.246698081 738829.00222902
555514.649475873738669.280006781555243.816142529738405.391117916
#Sta/Elev= 30
9300.878226.79299437.768223.49779519.187223.17779546.327224.67519600.607224.8568
9614.212221.88469636.456219.9231 9764.61215.71999821.101211.18889877.071 209.812
9930.079210.09539942.359 207.829 9946.14205.89829966.918190.52939979.197182.7425
9997.832181.552710016.04183.899910040.59 194.01410052.87200.633110065.15200.7627
10077.43198.215210083.99 198.14510100.87200.981710182.61199.003610452.71201.5704
10550.44200.883110592.33202.3385 10676.1 201.36610691.17203.9863 10733.6238.4388
#Mann= 3 , 0 , 0
9300.878   0.075       09300.878   0.075       0 10733.6   0.075       0
#XS Ineff= 2 , 0
       0                10062.09       0
Bank Sta=9300.878,10733.6
Exp/Cntr=0.3,0.1

Type RM Length L Ch R = 1 ,9801.378,238.972900,238.972900,238.972900
XS GIS Cut Line= 6
556981.314292268 739932.59617076556653.472115243739675.463036554
556308.991504445739347.733585865 555358.92128355738237.900243088
 555088.54309439737999.004634416554731.663337583737749.605757424
#Sta/Elev= 30
8424.669360.75788481.838359.5727 8544.42349.08778619.857351.51988717.085345.6244
 8761.17320.5153 8795.46318.95048811.029313.37168842.149291.96599208.196230.8379
9415.629223.51939593.723225.86419625.157218.10499923.813211.05669949.968  208.59
9988.857181.4725    9999181.076810019.83 181.75110050.81 197.33610241.74193.4072
10350.77198.658210684.68199.428610852.66247.4467 11020.2318.134711067.03312.8133
11169.36262.483311194.57 254.47711313.21245.1063 11452.5274.495411575.33352.8235
#Mann= 3 , 0 , 0
8424.669   0.075       08424.669   0.075       011575.33   0.075       0
#XS Ineff= 2 , 0
       0                10113.56       0
Bank Sta=8424.669,11575.33
Exp/Cntr=0.3,0.1

Type RM Length L Ch R = 1 ,9562.405,238.972800,238.972800,238.972800
XS GIS Cut Line= 6
557144.063535607739830.120547028556390.281376654739167.247007353
555900.981393215738414.102186751555660.497343688738123.950197177
555333.937799351  737842.2681597 554966.46723812737607.441548653
#Sta/Elev= 30
8423.799366.69218632.906371.29868760.039 365.5988837.475346.55898860.046332.1516
8966.925 313.9049023.404288.10619157.305254.45259275.466244.87619311.605248.6514
 9338.76 242.4169446.103235.49819575.871 233.0829601.453215.75439937.399209.0114
9948.592205.21449970.977181.40319993.363 176.58110026.77177.516310060.17193.5679
 10305.6186.919310340.97 195.37410480.04192.573810701.58197.129210988.88 219.267
11037.98214.8679 11085.8220.123211308.62222.290611461.83254.586911576.21311.8194
#Mann= 3 , 0 , 0
8423.799   0.075       08423.799   0.075       011576.21   0.075       0
#XS Ineff= 2 , 0
       0                10339.55       0
Bank Sta=8423.799,11576.21
Exp/Cntr=0.3,0.1

Type RM Length L Ch R = 1 ,9323.433,238.972900,238.972900,238.972900
XS GIS Cut Line= 6
557387.529472829739674.124786513556941.646082246739347.044408526
556631.375291037739055.435903765555844.795579346738018.113383999
555505.864420234737751.501140206555128.555440995737532.061147207
#Sta/Elev= 30
8423.442343.52818510.466346.46648703.478340.25078753.986   345.28793.472356.1944
8972.422357.04089011.786340.45289064.385336.07989091.448315.36359172.637312.2174
9282.806245.61569484.176245.29719501.164229.96939510.821227.41989652.997214.0942
9944.513  207.049968.209200.96089991.905170.723810003.75168.958610027.41172.6906
10054.62188.0362 10439.3183.295710651.99189.812510757.19200.919811011.67209.2548
11152.76219.771611463.85221.095711478.76224.710211501.61246.661211576.57275.0789
#Mann= 3 , 0 , 0
8423.442  0.0742       08423.442  0.0742       011576.57  0.0742       0
#XS Ineff= 2 , 0
       0                10202.23       0
Bank Sta=8423.442,11576.57
Exp/Cntr=0.3,0.1

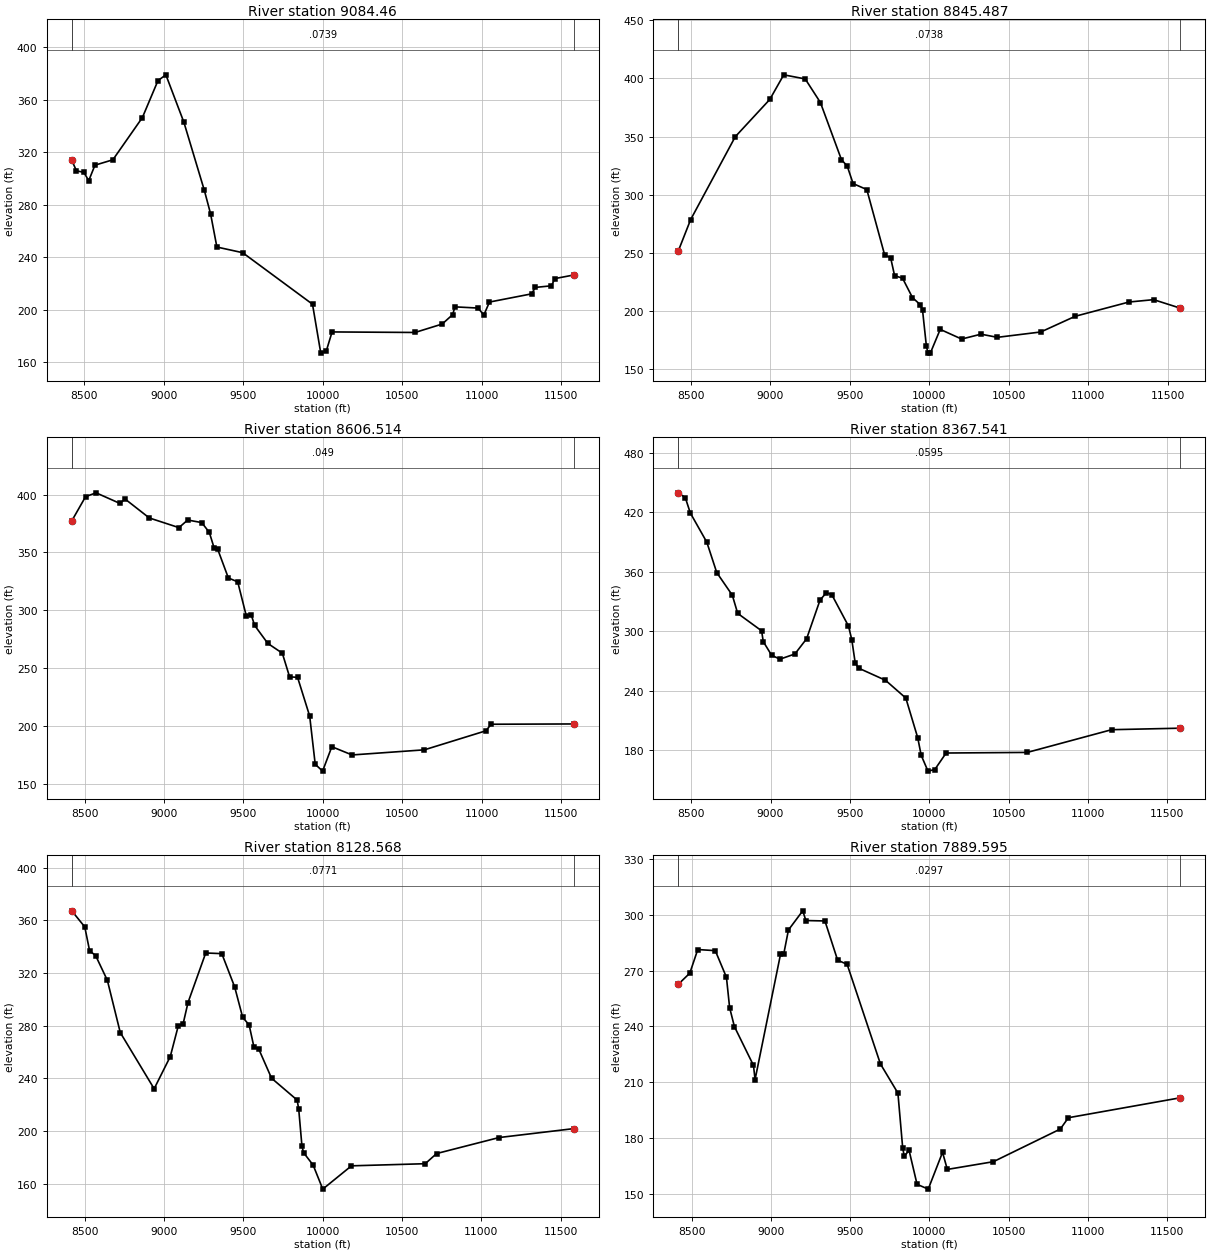
Type RM Length L Ch R = 1 , 9084.46,238.972900,238.972900,238.972900
XS GIS Cut Line= 6
557670.316346863739469.372550022 557267.86820942739213.115867155
  556861.5604143738888.115138678556275.597365027738191.326243398
556002.601720209737931.514477848555258.111796892 737482.75711415
#Sta/Elev= 30
8420.557313.94268449.981305.86778496.471304.7715 8527.25298.39898566.443310.1999
8679.095314.31398864.885346.54458962.952374.72399012.633379.12839126.017342.9304
9254.749290.93929293.706273.21329333.581247.75649495.718243.44519935.176204.1371
9987.263166.819410022.39168.634410058.26182.9897 10580.4182.580610751.01189.0047
10817.13196.205510831.14 202.11810977.15 201.19711012.96 195.84811048.55205.7845
11314.13212.045511336.83 216.95311438.15218.176311460.54223.694311579.45226.4413
#Mann= 3 , 0 , 0
8420.557  0.0739       08420.557  0.0739       011579.45  0.0739       0
#XS Ineff= 2 , 0
       0                 10090.6       0
Bank Sta=8420.557,11579.45
Exp/Cntr=0.3,0.1

Type RM Length L Ch R = 1 ,8845.487,238.972800,238.972800,238.972800
XS GIS Cut Line= 6
 557984.69461448739128.879406489557524.631321451738888.835838235
557146.368583381738653.305415232556031.032039417737817.932976536
555718.889597245737636.772081327555322.168634636737446.569850804
#Sta/Elev= 30
8420.093251.61998497.726278.57048778.891349.87038996.551381.94879084.026403.0449
9219.216399.51679314.777379.27589447.247330.18839483.709324.65069520.622309.6167
 9606.83 304.512 9719.28 248.2959756.765245.95259781.756230.54529831.736228.3941
9894.212211.72659944.193205.49489957.537201.00559981.678170.23219990.893 164.516
10006.64164.029910068.89184.427510203.52176.122410325.61180.306310428.51177.5929
10701.74182.193110918.37195.6746 11256.6207.917111411.94209.9561 11579.9202.6425
#Mann= 3 , 0 , 0
8420.093  0.0738       08420.093  0.0738       0 11579.9  0.0738       0
#XS Ineff= 2 , 0
       0                10073.69       0
Bank Sta=8420.093,11579.9
Exp/Cntr=0.3,0.1

Type RM Length L Ch R = 1 ,8606.514,238.972900,238.972900,238.972900
XS GIS Cut Line= 6
558195.984326438738771.123716788557447.391654736738447.557795456
557053.582424433738244.832630191556211.177532439737772.326545716
555762.409329333737561.174829711555355.492884878 737391.17435378
#Sta/Elev= 30
8419.111377.21468506.138398.1802 8572.19401.46898722.221392.33018754.768396.1131
8907.223379.76419093.949371.40339149.159377.98439237.528375.74989285.329367.2898
9315.778353.74619338.135352.72839405.206327.90539464.144324.55429517.714295.3963
9549.469295.92779570.801286.88039653.567271.37699744.974262.9213 9790.83242.4675
9841.074242.04199917.329208.5731 9952.17166.96259998.625161.019310056.83182.1151
10184.31174.992110639.56179.423511027.09195.866511060.07201.527611580.89201.7745
#Mann= 3 , 0 , 0
8419.111   0.049       08419.111   0.049       011580.89   0.049       0
#XS Ineff= 2 , 0
       0                10060.74       0
Bank Sta=8419.111,11580.89
Exp/Cntr=0.3,0.1

Type RM Length L Ch R = 1 ,8367.541,238.972800,238.972800,238.972800
XS GIS Cut Line= 6
558387.747367872 738372.09113652557846.377084375738208.768633707
 557354.90352672738047.239443845556695.131050578737801.483295454
556151.698861514737619.718793138555397.190904108737347.072299842
#Sta/Elev= 30
 8418.87439.5439 8463.42434.68398494.685419.28588598.903389.71478661.433359.0815
8759.378336.27368793.346317.90488943.938300.30798954.402289.43889006.809275.7183
9059.333271.67659153.877276.97219227.424292.32099311.785331.23969351.202338.7207
  9385.6336.91029491.051305.13529512.188291.1851 9533.37268.04069554.553262.6764
9724.243250.40449852.302232.44949927.398192.35119948.854174.82939991.766158.7357
10034.77160.354810106.11177.009510617.21 177.61911148.52200.542811581.12202.0687
#Mann= 3 , 0 , 0
 8418.87  0.0595       0 8418.87  0.0595       011581.12  0.0595       0
#XS Ineff= 2 , 0
       0                10146.61       0
Bank Sta=8418.87,11581.12
Exp/Cntr=0.3,0.1

Type RM Length L Ch R = 1 ,8128.568,238.972900,238.972900,238.972900
XS GIS Cut Line= 6
558505.627169492  737902.3105312557421.871520302737709.167166754
556582.620061058737609.262963647556363.956042411737573.901957365
555926.528677199737465.029681501555405.716965243737300.740319106
#Sta/Elev= 30
 8417.52367.18978499.514354.97568530.022336.82778567.704333.28868641.888 314.431
8723.244274.81598936.805232.1642  9038.5256.61229089.348280.12649119.822281.6503
 9150.27297.59019261.913 335.2059363.303334.7004 9444.33309.45429494.972286.2926
9535.447280.63729565.762263.90299596.078262.32569676.884240.17469838.205223.5925
9848.287216.52419868.452188.66349878.535183.71199939.103174.22339999.745156.0026
10180.65173.682510645.66175.290310717.27 183.00311111.08195.148411582.44201.9241
#Mann= 3 , 0 , 0
 8417.52  0.0771       0 8417.52  0.0771       011582.44  0.0771       0
#XS Ineff= 2 , 0
       0                10195.61       0
Bank Sta=8417.52,11582.44
Exp/Cntr=0.3,0.1

Type RM Length L Ch R = 1 ,7889.595,102.959800,102.959800,102.959800
XS GIS Cut Line= 6
558487.597992787737458.402859937557454.553430429737385.254647669
556635.732074182737440.291767704556377.215120037737437.373568044
555971.493339719737380.955069352 555350.27334015737221.347081852
#Sta/Elev= 30
8416.269 262.6318489.221268.61378539.465281.31448650.001 280.7098720.343 266.427
8740.417250.11828770.516 239.9488890.914219.07618900.947211.45969061.402278.7094
9081.436278.71069111.487291.81539201.641302.09969221.675296.88419341.744296.6558
9421.778275.59849481.792273.36529691.872219.86199802.114204.2105 9832.24 174.783
9842.282 170.2719872.496173.45589922.941155.2128  9993.4152.627410083.69172.3918
10113.84163.212510404.38167.358510826.78184.908510877.51190.980111583.72201.6899
#Mann= 3 , 0 , 0
8416.269  0.0297       08416.269  0.0297       011583.72  0.0297       0
#XS Ineff= 2 , 0
       09793.695        10076.72       0
Bank Sta=8416.269,11583.72
Exp/Cntr=0.3,0.1

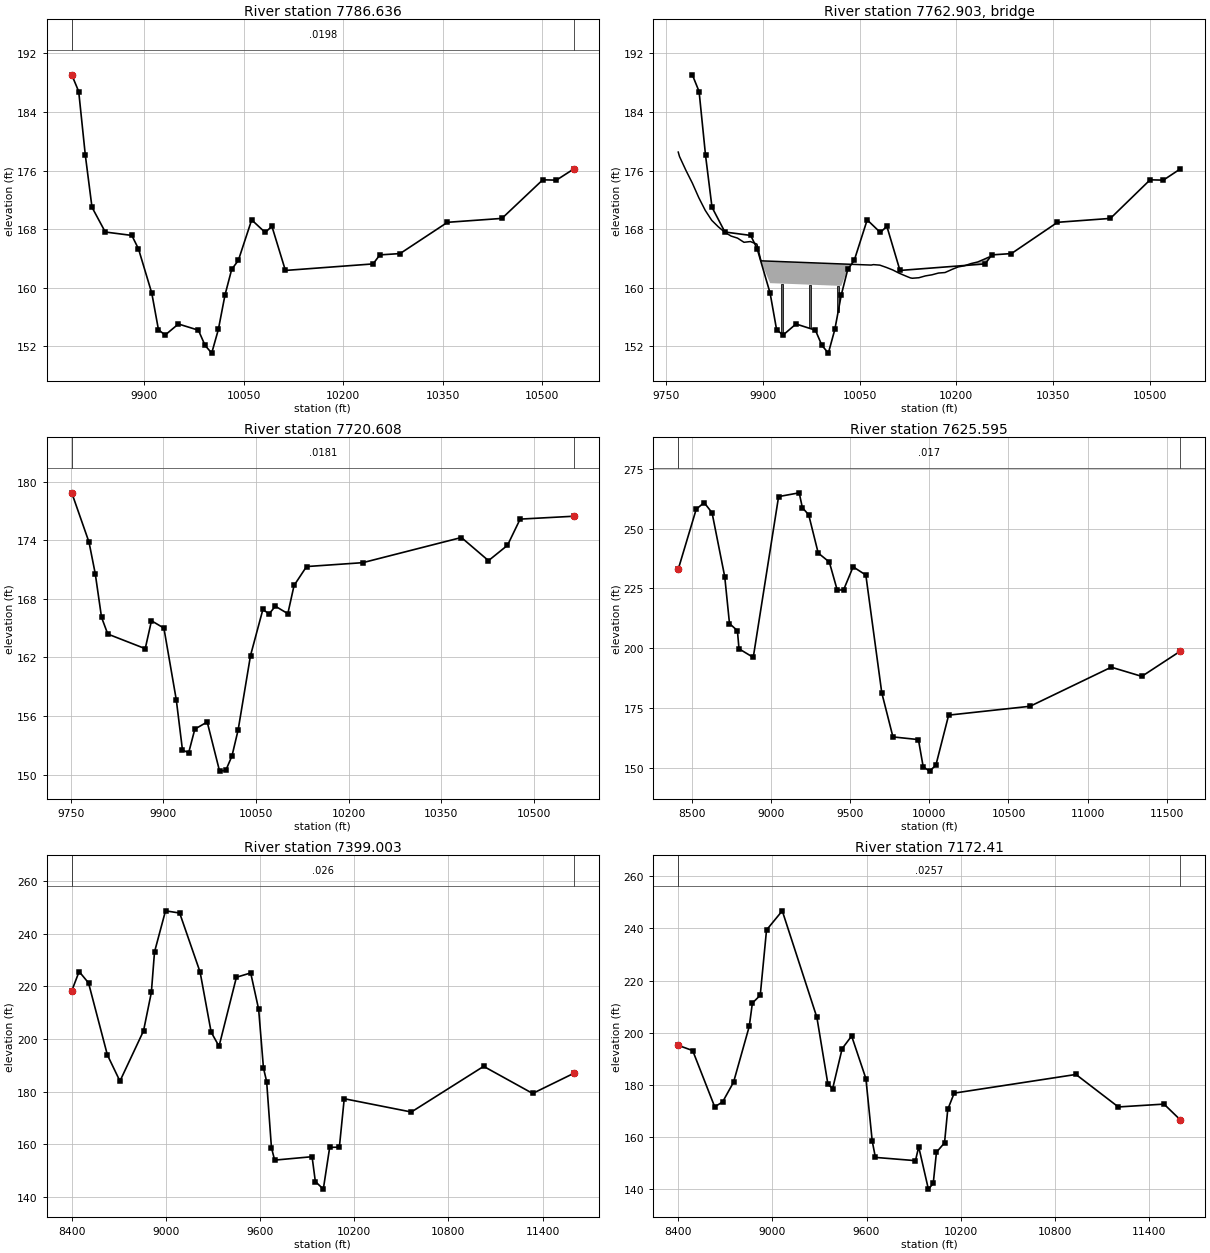
Type RM Length L Ch R = 1 ,7786.636,66.027500,66.027500,66.027500
XS GIS Cut Line= 5
557115.458913118737309.608409449557024.440693766737304.817976847
556848.392295837737320.386882797  556586.1161111737369.488816917
556369.349036098737419.788359195
#Sta/Elev= 30
9790.388189.06969800.862186.78699810.875178.05449820.889170.98249840.917167.6037
9880.972167.1373 9891.01165.30119911.088159.24629921.127154.26469931.166153.5299
9951.244155.04349981.361154.1974  9991.4152.126310001.44151.064210011.48154.2919
10021.52 159.01610031.56162.4979 10041.6 163.72610061.72169.262610082.07167.5445
10092.24168.383110112.59162.355610244.85163.247510255.02164.478810285.54164.6592
10357.04168.929610439.17169.462710500.76174.732510521.29174.687210547.63176.2181
#Mann= 3 , 0 , 0
9790.388  0.0198       09790.388  0.0198       010547.63  0.0198       0
#XS Ineff= 2 , 0
       09823.294        10074.97       0
Bank Sta=9790.388,10547.63
Exp/Cntr=0.3,0.1

Type RM Length L Ch R = 3 ,7762.903,,,
BEGIN DESCRIPTION:
END DESCRIPTION:
Bridge Culvert--1,0,-1,-1, 0
Deck Dist Width WeirC Skew NumUp NumDn MinLoCord MaxHiCord MaxSubmerge Is_Ogee
20.054450,25.918600,2.6,0, 43, 43, , , 0.95, 0, 0,0,,
 9768.49 9770.43 9780.44 9790.45 9800.46 9810.46 9820.47 9830.48 9840.49 9850.49
 9860.50 9870.51 9880.52 9883.84 9887.64 9887.64 9890.55 9896.8510058.5810058.58
10067.9610071.3010081.3510091.3910101.4310104.1010111.5410121.6710128.7110131.80
10141.9310152.0610162.2010172.3310182.4610190.9510192.5910202.7210212.8510222.99
10233.1210243.2510250.36
  178.52  177.92  176.02  174.27  172.28  170.55  169.20  168.33  167.59  167.05
  166.77  166.20  166.30  166.18  166.05  166.05  165.95  163.67  163.12  163.12
  163.09  163.15  163.08  162.77  162.42  162.30  161.97  161.59  161.34  161.29
  161.36  161.61  161.76  162.00  162.07  162.40  162.47  162.83  163.00  163.30
  163.51  163.89  164.17
 -821.48 -822.08 -823.98 -825.73 -827.72 -829.45 -830.80 -831.67 -832.41 -832.95
 -833.23 -833.80 -833.70 -833.82 -833.95  163.05  162.95  160.67  160.12 -836.88
 -836.91 -836.85 -836.92 -837.23 -837.58 -837.70 -838.03 -838.41 -838.66 -838.71
 -838.64 -838.39 -838.24 -838.00 -837.93 -837.60 -837.53 -837.17 -837.00 -836.70
 -836.49 -836.11 -835.83
 9768.49 9770.43 9780.44 9790.45 9800.46 9810.46 9820.47 9830.48 9840.49 9850.49
 9860.50 9870.51 9880.52 9883.84 9890.55 9892.24 9892.24 9896.8510063.1810063.18
10067.9610071.3010081.3510091.3910101.4310104.1010111.5410121.6710128.7110131.80
10141.9310152.0610162.2010172.3310182.4610190.9510192.5910202.7210212.8510222.99
10233.1210243.2510250.36
  178.52  177.92  176.02  174.27  172.28  170.55  169.20  168.33  167.59  167.05
  166.77  166.20  166.30  166.18  165.95  165.34  165.34  163.67  163.11  163.11
  163.09  163.15  163.08  162.77  162.42  162.30  161.97  161.59  161.34  161.29
  161.36  161.61  161.76  162.00  162.07  162.40  162.47  162.83  163.00  163.30
  163.51  163.89  164.17
 -821.48 -822.08 -823.98 -825.73 -827.72 -829.45 -830.80 -831.67 -832.41 -832.95
 -833.23 -833.80 -833.70 -833.82 -834.05 -834.66  162.34  160.67  160.11 -836.89
 -836.91 -836.85 -836.92 -837.23 -837.58 -837.70 -838.03 -838.41 -838.66 -838.71
 -838.64 -838.39 -838.24 -838.00 -837.93 -837.60 -837.53 -837.17 -837.00 -836.70
 -836.49 -836.11 -835.83
Pier Skew, UpSta & Num, DnSta & Num=  ,9929.63, 2 ,9934.23, 2 , 0 , 0 , 0 ,,
    3.00    3.00
 -836.44  163.56
    3.00    3.00
 -836.46  163.54
Pier Skew, UpSta & Num, DnSta & Num=  ,9973.11, 2 ,9977.71, 2 , 0 , 0 , 0 ,,
    3.00    3.00
 -836.59  163.41
    3.00    3.00
 -836.60  163.40
Pier Skew, UpSta & Num, DnSta & Num=  ,10016.59, 2 ,10021.19, 2 , 0 , 0 , 0 ,,
    3.00    3.00
 -836.73  163.27
    3.00    3.00
 -836.75  163.25
BR Coef=-1 , 0 , 0 ,, 0 ,,,0.8,0,1,0,
WSPro=,,,, 1 ,,,, 0 ,,,, 0 ,,,,-1 ,-1 ,-1 , 0 , 0 , 0 , 0 , 0
BC Design=,, 0 ,, 0 ,,,,,,

Type RM Length L Ch R = 1 ,7720.608,95.012700,95.012700,95.012700
XS GIS Cut Line= 6
557152.584765762737220.985406399557012.464612305737242.542353094
556841.206646919737253.320826426556751.386035711 737266.49451609
 556570.54720518737295.237111658556350.187305689737345.536653936
#Sta/Elev= 30
9751.587178.86829779.517173.81249789.642 170.5789799.768166.12399809.893164.4006
9870.576162.90419880.686165.76189900.837165.00839920.877157.66789930.896152.5257
9940.916 152.2349950.936154.66199970.976 155.3929991.015150.357710001.03150.4311
10011.05151.903510021.07154.574810041.11162.197210061.15 166.91710071.23166.4623
10081.33167.254910101.55166.489410111.66169.377110131.87171.314110222.96171.7131
10382.72174.291310426.59171.920210457.36173.490510477.88176.175510564.87176.4706
#Mann= 3 , 0 , 0
9751.587  0.0181       09751.587  0.0181       010564.87  0.0181       0
#XS Ineff= 2 , 0
       09847.992        10081.21       0
Bank Sta=9751.587,10564.87
Exp/Cntr=0.3,0.1

Type RM Length L Ch R = 1 ,7625.595,226.592800,226.592800,226.592800
XS GIS Cut Line= 6
558488.361614216737110.371777869557927.195706219737094.051323847
557510.413379054737103.260899329556203.683553744737227.711182969
 555773.88104145737191.175296751555337.225553954737105.554553365
#Sta/Elev= 30
8415.107233.0064 8528.56 258.085  8578.6260.8736 8628.64256.60048708.682229.8995
8738.687210.34098788.697207.34168798.699199.79358888.717196.18319048.737263.3716
9178.742 264.9449198.742258.74189238.764255.75389298.812239.78349368.866236.0392
9418.941224.29499459.027224.40689519.205234.02249599.517230.60359700.125181.3925
9770.569162.97359931.459161.85139961.491150.510510001.52148.676610041.56151.1217
10122.26172.067310636.77175.776611148.83192.098811341.81188.260811584.89198.7917
#Mann= 3 , 0 , 0
8415.107   0.017       08415.107   0.017       011584.89   0.017       0
#XS Ineff= 2 , 0
       09870.343        10138.28       0
Bank Sta=8415.107,11584.89
Exp/Cntr=0.3,0.1

Type RM Length L Ch R = 1 ,7399.003,226.592700,226.592700,226.592700
XS GIS Cut Line= 6
558411.803481548736784.393301997557366.273479953736835.195481107
556505.679270718737025.505173164 556195.27219712737063.754274425
555803.135842195737057.676450654555246.382725412736978.653427368
#Sta/Elev= 30
8401.134218.27248447.941225.61018507.946221.27258627.956193.90878707.963183.9535
 8858.05 203.0328908.084217.69878928.097233.04058998.145  248.689088.315247.8417
9218.585 225.3669288.854202.57549339.061197.19829449.762223.43219540.709225.0734
9591.376211.25259621.921188.98379642.285183.79319672.831158.70929693.194153.9338
9931.631155.23079952.434145.803310003.23142.908510043.79158.769410105.49158.8694
10136.44177.268710563.84 172.217 11024.4189.569111336.57179.273811598.87186.9332
#Mann= 3 , 0 , 0
8401.134   0.026       08401.134   0.026       011598.87   0.026       0
#XS Ineff= 2 , 0
       09839.117                       0
Bank Sta=8401.134,11598.87
Exp/Cntr=0.3,0.1

Type RM Length L Ch R = 1 , 7172.41,226.592800,226.592800,226.592800
XS GIS Cut Line= 6
558357.070839366736563.139061301557261.100460998736638.935811951
556475.760943434736799.291442215556135.742052202736843.060806011
555640.081080231736848.542808312555181.930108324736806.345943394
#Sta/Elev= 30
8399.945195.17278492.094193.16188632.214171.61878682.257173.43268752.317181.0087
8852.497202.43538872.535 211.383 8922.63214.36498962.706239.40349062.949246.7473
 9283.71205.87989354.097180.2263 9384.28178.62029444.647193.89079505.038198.7551
9595.962182.44439636.373 158.4759656.641152.20949911.978150.96199932.567156.2629
9994.337140.045110025.19142.211210045.76 154.19110097.18157.791710117.75170.5872
10158.75176.849410934.85  184.0111205.06171.553211496.23 172.64311600.06166.5998
#Mann= 3 , 0 , 0
8399.945  0.0257       08399.945  0.0257       011600.06  0.0257       0
#XS Ineff= 2 , 0
       09819.396        10662.03       0
Bank Sta=8399.945,11600.06
Exp/Cntr=0.3,0.1

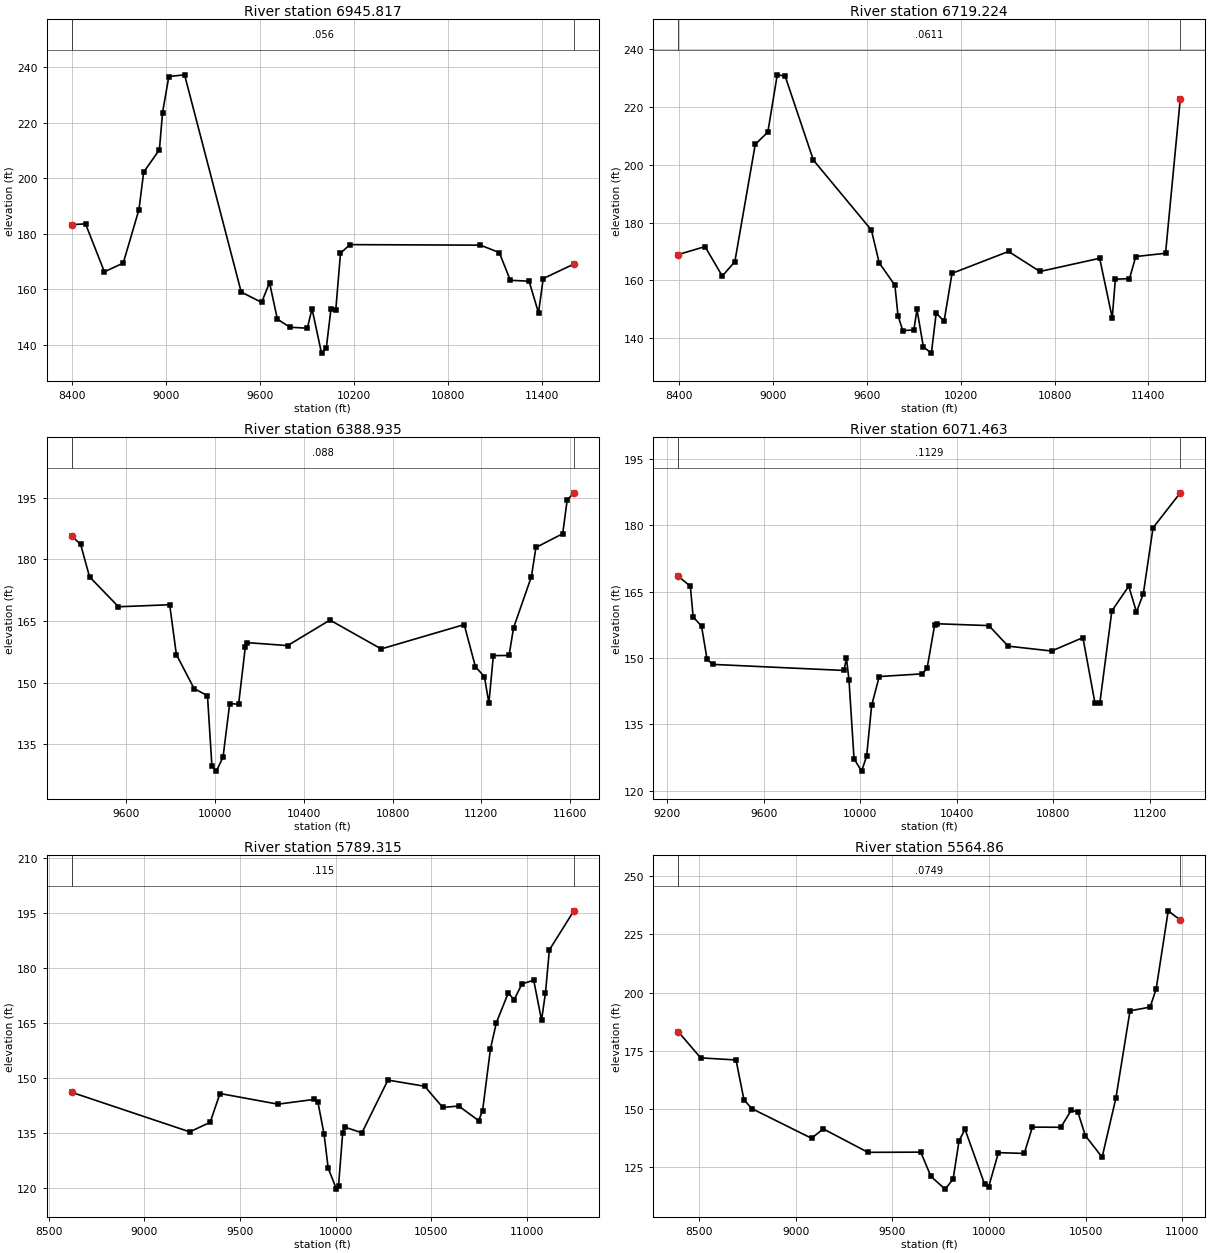
Type RM Length L Ch R = 1 ,6945.817,226.592800,226.592800,226.592800
XS GIS Cut Line= 6
 558322.69194468736388.073542903556931.338400791736488.750897236
556479.707604721736540.812924537555951.389098784736582.997968556
555590.652366472736596.229610998555129.902621318736584.705961833
#Sta/Elev= 30
8399.134183.2809 8486.97183.56568607.167166.31118727.403169.46118827.639188.7191
8857.709202.17998958.003210.22718978.063223.61359018.184 236.5739118.484237.1892
9479.566159.03929609.956155.30549660.107162.44859710.257149.28139790.497146.3657
9901.007146.01819931.227152.99199991.758137.050510022.03138.8402 10052.3153.0297
10082.58152.521910112.79173.016710173.13176.092311005.48175.899911125.52173.2279
11195.53163.259611315.53162.926611375.54151.544111405.56163.881711600.86169.0889
#Mann= 3 , 0 , 0
8399.134   0.056       08399.134   0.056       011600.86   0.056       0
#XS Ineff= 2 , 0
       09760.109        10436.86       0
Bank Sta=8399.134,11600.86
Exp/Cntr=0.3,0.1

Type RM Length L Ch R = 1 ,6719.224,330.289100,330.289100,330.289100
XS GIS Cut Line= 6
558325.683679848736244.474521839 557104.00023536736326.980189519
556880.265370404736313.698549449556543.557712696736255.543915791
556330.872053157 736248.03659636555130.724985083 736332.13009681
#Sta/Elev= 30
 8396.45168.91938567.548171.67038677.815161.47698758.056166.47268888.471207.0355
8968.727211.25419028.918231.06959079.078230.64569259.652201.5823 9630.13177.3995
 9680.15166.05649780.364158.31679800.446147.73839830.568142.64889901.314142.8152
9921.563149.92789962.305136.987710013.36134.836210043.96 148.57710094.87145.9465
10145.35162.422510506.11169.988310706.82163.062411088.42167.633211168.68147.0269
11188.74160.405311278.98160.588711319.05168.236511509.27169.366811603.57222.8576
#Mann= 3 , 0 , 0
 8396.45  0.0611       0 8396.45  0.0611       011603.57  0.0611       0
#XS Ineff= 2 , 0
       09744.023        10180.31       0
Bank Sta=8396.45,11603.57
Exp/Cntr=0.3,0.1

Type RM Length L Ch R = 1 ,6388.935,317.472500,317.472500,317.472500
XS GIS Cut Line= 6
557454.756825835736004.970864534557094.513770193735978.929197878
556621.423492461735961.568086758555931.674750835736019.368260652
555446.473951072736091.670873389555205.026101172736116.109395847
#Sta/Elev= 30
9356.133185.68079395.993183.66629436.098175.76859566.437 168.4819796.883168.9729
9826.903156.85779906.957148.54129966.997146.84219987.011129.666610007.02128.4631
10037.04131.872210067.06144.921210107.09144.737110137.11158.581610147.12159.7447
10327.63159.023710518.29165.2449 10749.1158.216211122.67  164.1411173.17153.8744
11213.53151.468711233.71145.0349 11253.9156.584711324.53 156.62411344.71 163.329
11425.28175.8383 11445.4182.912111566.02186.2697 11586.1194.451811616.19196.2203
#Mann= 3 , 0 , 0
9356.133   0.088       09356.133   0.088       011616.19   0.088       0
#XS Ineff= 2 , 0
       09906.469        10157.23       0
Bank Sta=9356.133,11616.19
Exp/Cntr=0.3,0.1

Type RM Length L Ch R = 1 ,6071.463,282.147600,282.147600,282.147600
XS GIS Cut Line= 5
 557378.34878996735832.643638775 556970.47263369735594.378865331
 556300.24293685735796.637531221555573.049123794735796.637531221
555393.124881297735822.679197893
#Sta/Elev= 30
9244.866168.45559295.069166.1985 9306.65159.27639341.394157.18549364.556149.6538
9387.719148.5469 9931.86147.17429942.306149.94599952.751 145.0069973.642127.2282
10004.98124.438510025.87127.805310046.76139.2969 10078.1145.802410255.67146.4036
10276.56147.6541 10307.9157.460910318.34 157.72410532.56157.307210612.56152.6675
10792.56151.565610922.56 154.58810972.56139.798810992.56139.770611042.56160.6277
11112.56166.209211144.51160.383711172.85164.476411213.27179.409311326.31187.2952
#Mann= 3 , 0 , 0
9244.866  0.1129       09244.866  0.1129       011326.31  0.1129       0
#XS Ineff= 2 , 0
       09877.471        10104.13       0
Bank Sta=9244.866,11326.31
Exp/Cntr=0.3,0.1

Type RM Length L Ch R = 1 ,5789.315,224.454700,224.454700,224.454700
XS GIS Cut Line= 6
557894.844631106735579.363224357557068.528406262735365.611284241
556756.916238248735353.105110317556061.117076516735621.347708285
555748.763385147735708.595383227555369.327864647735788.420589045
#Sta/Elev= 30
8620.965146.1322 9237.34135.37289343.845137.95869395.491145.81059698.188142.9148
9885.209144.19079906.817143.5366 9939.23134.78689960.838125.474110004.06119.7769
10014.87120.684410036.49135.0101 10047.3 136.67410137.04135.108910272.92 149.473
10464.84147.792210559.52142.021410642.93142.407610746.86138.431210767.52 141.121
10808.86158.042410839.86165.143210901.62 173.17310932.45171.3673 10973.4175.6598
11034.73176.682111075.62 165.78311096.07173.165511116.51184.909411244.44195.5646
#Mann= 3 , 0 , 0
8620.965   0.115       08620.965   0.115       011244.44   0.115       0
#XS Ineff= 2 , 0
       09842.019        10121.34       0
Bank Sta=8620.965,11244.44
Exp/Cntr=0.3,0.1

Type RM Length L Ch R = 1 , 5564.86,224.454600,224.454600,224.454600
XS GIS Cut Line= 6
558048.842170686734823.818294898 557368.86941433 734969.97592552
 556689.19678697735179.850872725556326.470047295735255.434638217
555876.722009718 735403.69857879555544.358363479735498.075879127
#Sta/Elev= 30
8392.372183.2775 8508.07172.00938691.367171.09568732.274154.00948773.261150.2105
9081.789137.47559142.716141.50699373.519131.43399646.849131.51769699.518121.0741
9772.604 115.6329814.132 119.8749844.957136.41399875.783141.34089977.425117.6996
9997.705116.507810048.55131.300110182.28130.965710224.19142.273510371.49  142.19
10424.21149.4187 10458.8148.905110498.03 138.62210584.89129.344810656.09154.6821
10729.28192.217110833.43193.808210864.57201.630310926.85235.1591 10989.4231.1919
#Mann= 3 , 0 , 0
8392.372  0.0749       08392.372  0.0749       0 10989.4  0.0749       0
#XS Ineff= 2 , 0
       09889.434        10283.61       0
Bank Sta=8392.372,10989.4
Exp/Cntr=0.3,0.1

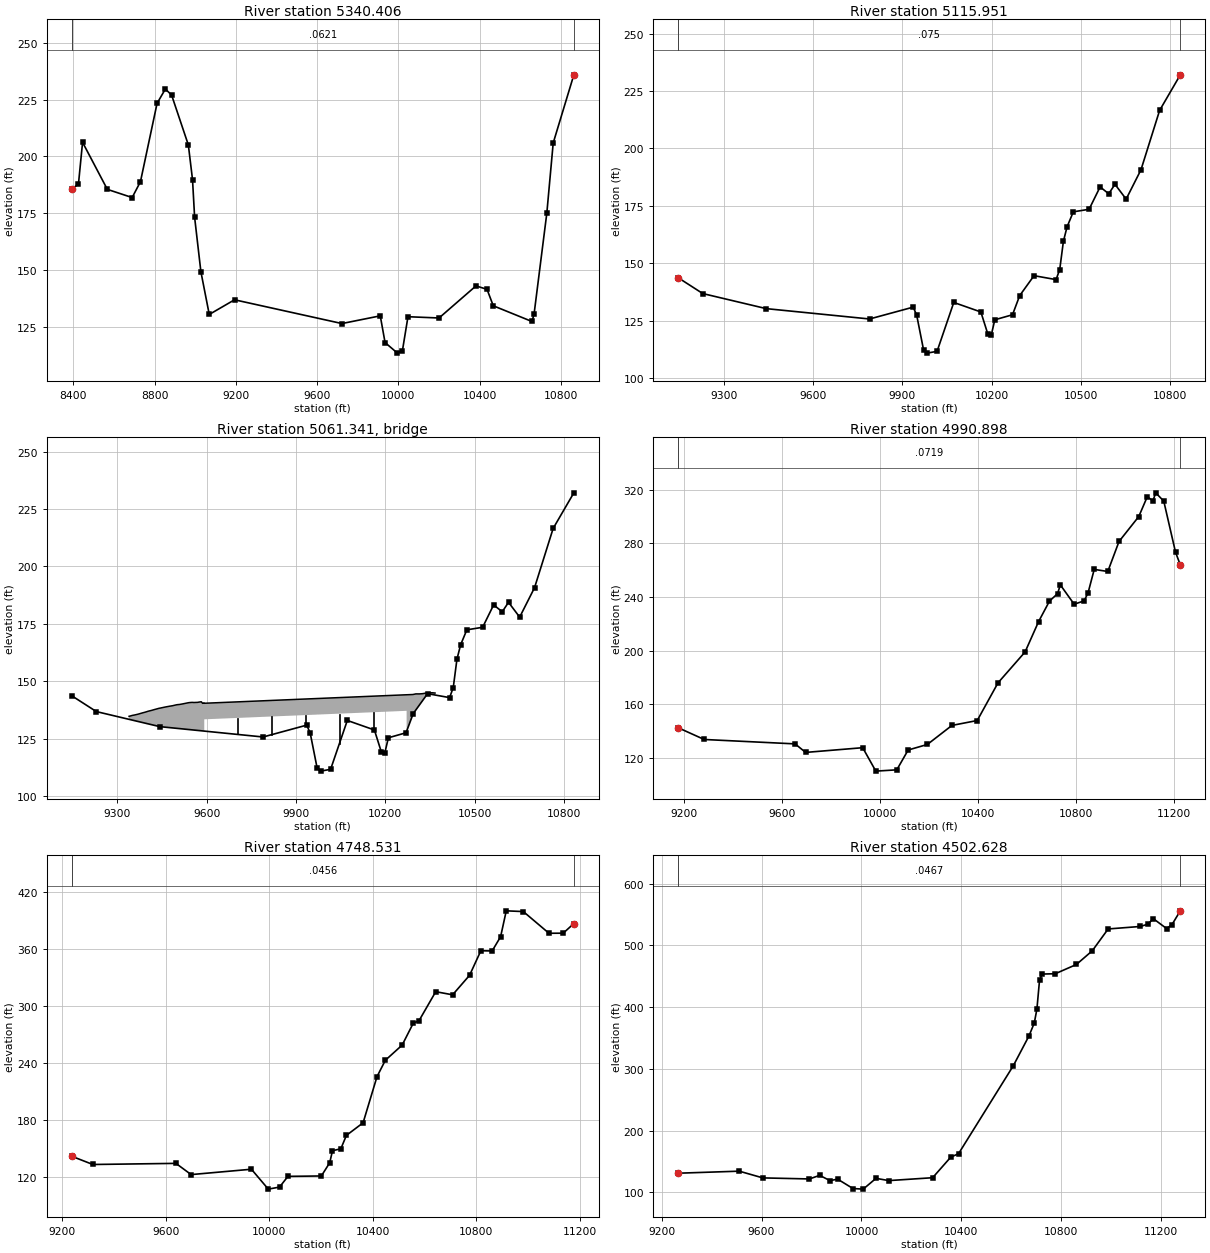
Type RM Length L Ch R = 1 ,5340.406,224.454600,224.454600,224.454600
XS GIS Cut Line= 6
557957.368040085734544.384863645557475.076357454734638.467045799
556968.548402756 734778.51228109556584.236012191734925.861106545
556249.991222531735113.651746064555627.696630269735327.448629707
#Sta/Elev= 30
8392.299185.62578425.154187.72278445.454206.16528567.314185.44318689.562181.8342
8730.459188.83518812.254223.33078853.152229.63968883.825226.95648966.181  205.01
 8986.77189.70738997.065173.15389027.948149.18649069.138130.34899193.632136.8112
9722.251126.34769911.061129.73879934.589117.99089995.651113.319810020.07114.3817
10047.41 129.35210200.36128.794310382.27142.931510436.61141.411110467.35134.1717
10657.52127.259810668.05130.390510731.03174.991610762.39205.855910864.03235.8823
#Mann= 3 , 0 , 0
8392.299  0.0621       08392.299  0.0621       010864.03  0.0621       0
#XS Ineff= 2 , 0
       0 9863.42        10203.25       0
Bank Sta=8392.299,10864.03
Exp/Cntr=0.3,0.1

Type RM Length L Ch R = 1 ,5115.951,125.052800,125.052800,125.052800
XS GIS Cut Line= 6
556925.025554836734203.887967736556662.614908189734540.205863103
556497.839078486734707.624914661556391.114735276734785.475418329
556049.905675203734984.317107216555649.330863357735279.187648192
#Sta/Elev= 30
9146.629 143.6619229.159136.77419442.483 130.2119789.384125.70679935.881130.8677
9947.621127.41579970.681112.3043 9982.21110.832610016.12111.608510072.28132.9095
10163.28128.7588 10186.7119.135910198.44118.841310210.18125.358510269.61127.5476
10293.67135.883410341.92 144.57310415.89142.856710428.22147.259210440.55159.5403
10452.88165.839510473.83172.389110526.85173.488710563.87183.251110592.73180.2492
10613.84 184.37210651.32177.918110701.29190.747910763.75216.5558 10833.3232.0641
#Mann= 3 , 0 , 0
9146.629   0.075       09146.629   0.075       0 10833.3   0.075       0
#XS Ineff= 2 , 0
       09910.478        10093.53       0
Bank Sta=9146.629,10833.3
Exp/Cntr=0.3,0.1

Type RM Length L Ch R = 3 ,5061.341,,,
BEGIN DESCRIPTION:
END DESCRIPTION:
Bridge Culvert--1,0,-1,-1, 0
Deck Dist Width WeirC Skew NumUp NumDn MinLoCord MaxHiCord MaxSubmerge Is_Ogee
30.538250,63.976300,2.6,0, 55, 55, , , 0.95, 0, 0,0,,
 9339.05 9344.68 9349.78 9356.46 9368.25 9368.68 9380.03 9387.59 9391.81 9403.59
 9406.50 9415.38 9425.41 9427.16 9438.94 9444.31 9450.73 9462.51 9463.22 9474.29
 9482.13 9486.07 9497.86 9501.04 9509.64 9519.94 9521.42 9533.21 9538.85 9544.99
 9550.78 9557.05 9557.07 9569.43 9574.06 9581.80 9586.20 9590.40 9591.06 9591.75
 9591.7510271.5410271.5410292.7210302.4410313.6210314.6110315.0410324.8010335.98
10337.4010347.1610358.3410359.7710367.02
  134.71  134.90  135.10  135.26  135.61  135.62  136.05  136.33  136.46  136.94
  137.03  137.32  137.70  137.75  138.18  138.31  138.49  138.81  138.83  139.09
  139.26  139.35  139.71  139.78  139.89  140.14  140.18  140.49  140.64  140.73
  140.78  140.73  140.73  140.79  140.91  141.05  140.37  140.58  140.40  140.40
  140.40  144.10  144.10  144.21  144.48  144.47  144.47  144.48  144.57  144.82
  144.84  144.95  144.96  144.95  144.85
 -865.29 -865.10 -864.90 -864.74 -864.39 -864.38 -863.95 -863.67 -863.54 -863.06
 -862.97 -862.68 -862.30 -862.25 -861.82 -861.69 -861.51 -861.19 -861.17 -860.91
 -860.74 -860.65 -860.29 -860.22 -860.11 -859.86 -859.82 -859.51 -859.36 -859.27
 -859.22 -859.27 -859.27 -859.21 -859.09 -858.95 -859.63 -859.42 -859.60 -859.60
  133.40  137.10 -855.90 -855.79 -855.52 -855.53 -855.53 -855.52 -855.43 -855.18
 -855.16 -855.05 -855.04 -855.05 -855.15
 9339.05 9344.68 9349.78 9356.46 9368.25 9368.68 9380.03 9387.59 9391.81 9403.59
 9406.50 9415.38 9425.41 9427.16 9438.94 9444.31 9450.73 9462.51 9463.22 9474.29
 9482.13 9486.07 9497.86 9501.04 9509.64 9519.94 9521.42 9533.21 9538.85 9544.99
 9550.78 9557.05 9557.07 9569.43 9574.06 9581.80 9586.20 9590.40 9591.06 9612.97
 9612.9710292.7210292.7610292.7610302.4410313.6210314.6110315.0410324.8010335.98
10337.4010347.1610358.3410359.7710367.02
  134.71  134.90  135.10  135.26  135.61  135.62  136.05  136.33  136.46  136.94
  137.03  137.32  137.70  137.75  138.18  138.31  138.49  138.81  138.83  139.09
  139.26  139.35  139.71  139.78  139.89  140.14  140.18  140.49  140.64  140.73
  140.78  140.73  140.73  140.79  140.91  141.05  140.37  140.58  140.40  140.51
  140.51  144.21  144.21  144.21  144.48  144.47  144.47  144.48  144.57  144.82
  144.84  144.95  144.96  144.95  144.85
 -865.29 -865.10 -864.90 -864.74 -864.39 -864.38 -863.95 -863.67 -863.54 -863.06
 -862.97 -862.68 -862.30 -862.25 -861.82 -861.69 -861.51 -861.19 -861.17 -860.91
 -860.74 -860.65 -860.29 -860.22 -860.11 -859.86 -859.82 -859.51 -859.36 -859.27
 -859.22 -859.27 -859.27 -859.21 -859.09 -858.95 -859.63 -859.42 -859.60 -859.49
  133.51  137.21  137.21 -855.79 -855.52 -855.53 -855.53 -855.52 -855.43 -855.18
 -855.16 -855.05 -855.04 -855.05 -855.15
Pier Skew, UpSta & Num, DnSta & Num=  ,9703.72, 2 ,9724.93, 2 , 0 , 0 , 0 ,,
    4.00    4.00
 -858.99  141.01
    4.00    4.00
 -858.88  141.12
Pier Skew, UpSta & Num, DnSta & Num=  ,9817.68, 2 ,9838.90, 2 , 0 , 0 , 0 ,,
    4.00    4.00
 -858.37  141.63
    4.00    4.00
 -858.26  141.74
Pier Skew, UpSta & Num, DnSta & Num=  ,9931.65, 2 ,9952.86, 2 , 0 , 0 , 0 ,,
    4.00    4.00
 -857.75  142.25
    4.00    4.00
 -857.64  142.36
Pier Skew, UpSta & Num, DnSta & Num=  ,10045.61, 2 ,10066.83, 2 , 0 , 0 , 0 ,,
    4.00    4.00
 -857.13  142.87
    4.00    4.00
 -857.02  142.98
Pier Skew, UpSta & Num, DnSta & Num=  ,10159.58, 2 ,10180.79, 2 , 0 , 0 , 0 ,,
    4.00    4.00
 -856.51  143.49
    4.00    4.00
 -856.40  143.60
BR Coef=-1 , 0 , 0 ,, 0 ,,,0.8,0,1,0,
WSPro=,,,, 1 ,,,, 0 ,,,, 0 ,,,,-1 ,-1 ,-1 , 0 , 0 , 0 , 0 , 0
BC Design=,, 0 ,, 0 ,,,,,,

Type RM Length L Ch R = 1 ,4990.898,242.367600,242.367600,242.367600
XS GIS Cut Line= 6
556901.297761589734191.265378892556651.297761679734305.848712251
556479.422761679734545.432045579556367.443594903734654.807045579
555600.148059994 735041.00984633555197.985908747735268.526596606
#Sta/Elev= 30
  9177.5142.5673 9283.43133.84739654.235130.56859697.113124.21189930.011127.7262
9983.528110.279110069.08111.242710115.43126.012710193.69130.128910294.06144.3213
10397.21147.972710481.95176.017910592.47199.049110647.73221.706810691.93236.9122
10725.09242.480510736.14249.010110792.62234.570810833.55237.097910849.62243.2151
10874.48260.516610929.85258.9623 10975.7281.326111056.28299.892911090.85314.6246
11113.89311.566911125.42317.538511158.18311.369411206.07273.355611225.67263.8461
#Mann= 3 , 0 , 0
  9177.5  0.0719       0  9177.5  0.0719       011225.67  0.0719       0
#XS Ineff= 2 , 0
       0 9918.79         10147.9       0
Bank Sta=9177.5,11225.67
Exp/Cntr=0.3,0.1

Type RM Length L Ch R = 1 ,4748.531,245.902800,245.902800,245.902800
XS GIS Cut Line= 6
556892.922844173734181.627721863556778.044710606734217.027120858
556680.005078971734270.268798411556560.619314253734326.843729958
555570.177460939734731.000788808555107.723489076734938.692849815
#Sta/Elev= 30
9235.945141.94399317.484133.28389638.534134.46599697.358122.64119930.332128.2979
9995.546107.326510038.97109.486810071.52120.773810200.68121.191510232.94 135.115
10243.69147.805810275.95149.835310297.46163.946810361.97177.224610415.73225.8443
10448.01 243.11810512.92259.0935 10556.2282.349210577.84284.656510642.75315.3782
   10708312.087610773.48332.630410817.13 358.51110860.78358.294210893.52373.3181
10915.35400.583810981.34399.800311080.46 376.94311135.53377.028711176.59387.1782
#Mann= 3 , 0 , 0
9235.945  0.0456       09235.945  0.0456       011176.59  0.0456       0
#XS Ineff= 2 , 0
       09906.664        10099.45       0
Bank Sta=9235.945,11176.59
Exp/Cntr=0.3,0.1

Type RM Length L Ch R = 1 ,4502.628,221.628000,221.628000,221.628000
XS GIS Cut Line= 6
556812.322692589734036.309327943556625.907125503734111.268741772
556433.631373614734171.099611431555940.049358875734286.674269691
555496.655836642734412.628890663  554893.6098797734622.646097569
#Sta/Elev= 30
9266.723130.97339510.805134.27889605.137123.37379791.609121.6605 9832.75127.5165
 9873.88118.95459904.581121.34459965.983106.135810006.91 105.17910058.05122.6319
 10109.4118.998610284.65123.668610357.17156.975710388.35162.576710607.48305.0706
 10670.4353.524310691.44374.385910701.95396.875910712.47443.760410722.98453.6129
10775.57454.156310859.97469.141810923.46491.291410986.95526.677711114.35530.6828
11146.28 534.36211167.57543.401711220.79527.342211242.17533.586511275.76556.0569
#Mann= 3 , 0 , 0
9266.723  0.0467       09266.723  0.0467       011275.76  0.0467       0
#XS Ineff= 2 , 0
       09881.344        10072.87       0
Bank Sta=9266.723,11275.76
Exp/Cntr=0.3,0.1