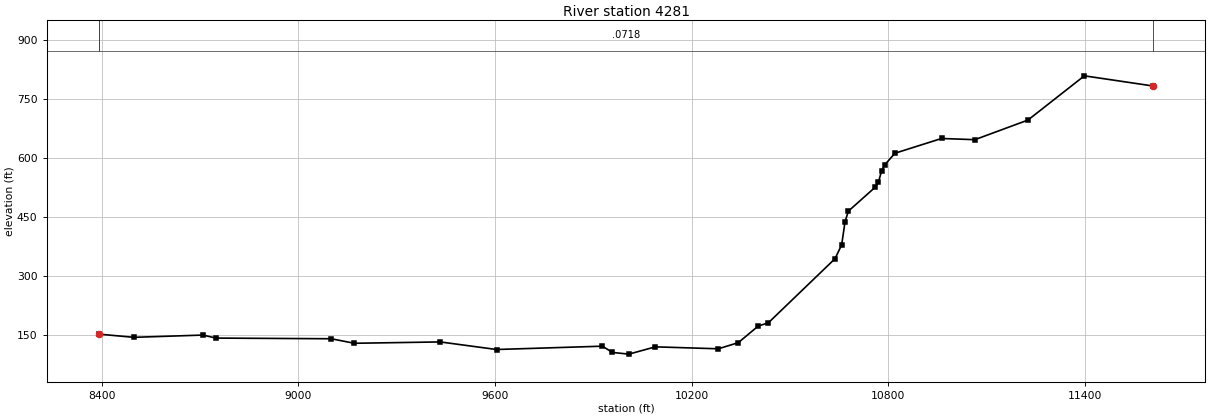
HEC-RAS study 1761_ras.prj: 1761

--- 1761_ras.g01 (geometry) --- (continued)

Type RM Length L Ch R = 1 ,    4281,0.000000,0.000000,0.000000
XS GIS Cut Line= 6
 557679.97291836733841.804230893557193.301950613 733883.62110806
 556853.74233437733919.310561657555967.973146549734042.583011665
555106.379090899734199.201022886554498.598848583734296.128102569
#Sta/Elev= 30
8392.252152.77138497.611144.75898708.385150.49568748.532142.8313 9100.13141.1203
9170.572129.62639432.759 133.0359604.629113.77579928.011122.23239958.244106.3116
10008.63102.011710089.27  120.5310281.74  115.5910342.64131.196110403.71 173.589
10434.25 181.55710637.81344.753910658.17379.971210668.35438.154710678.53465.6974
10759.93526.2082 10770.1538.831710780.26568.644710790.42584.358310820.91613.1425
10963.18650.660511064.63647.584611226.83697.507911398.98810.052511607.74784.3081
#Mann= 3 , 0 , 0
8392.252  0.0718       08392.252  0.0718       011607.74  0.0718       0
#XS Ineff= 2 , 0
       09901.044        10106.42       0
Bank Sta=8392.252,11607.74
Exp/Cntr=0.3,0.1